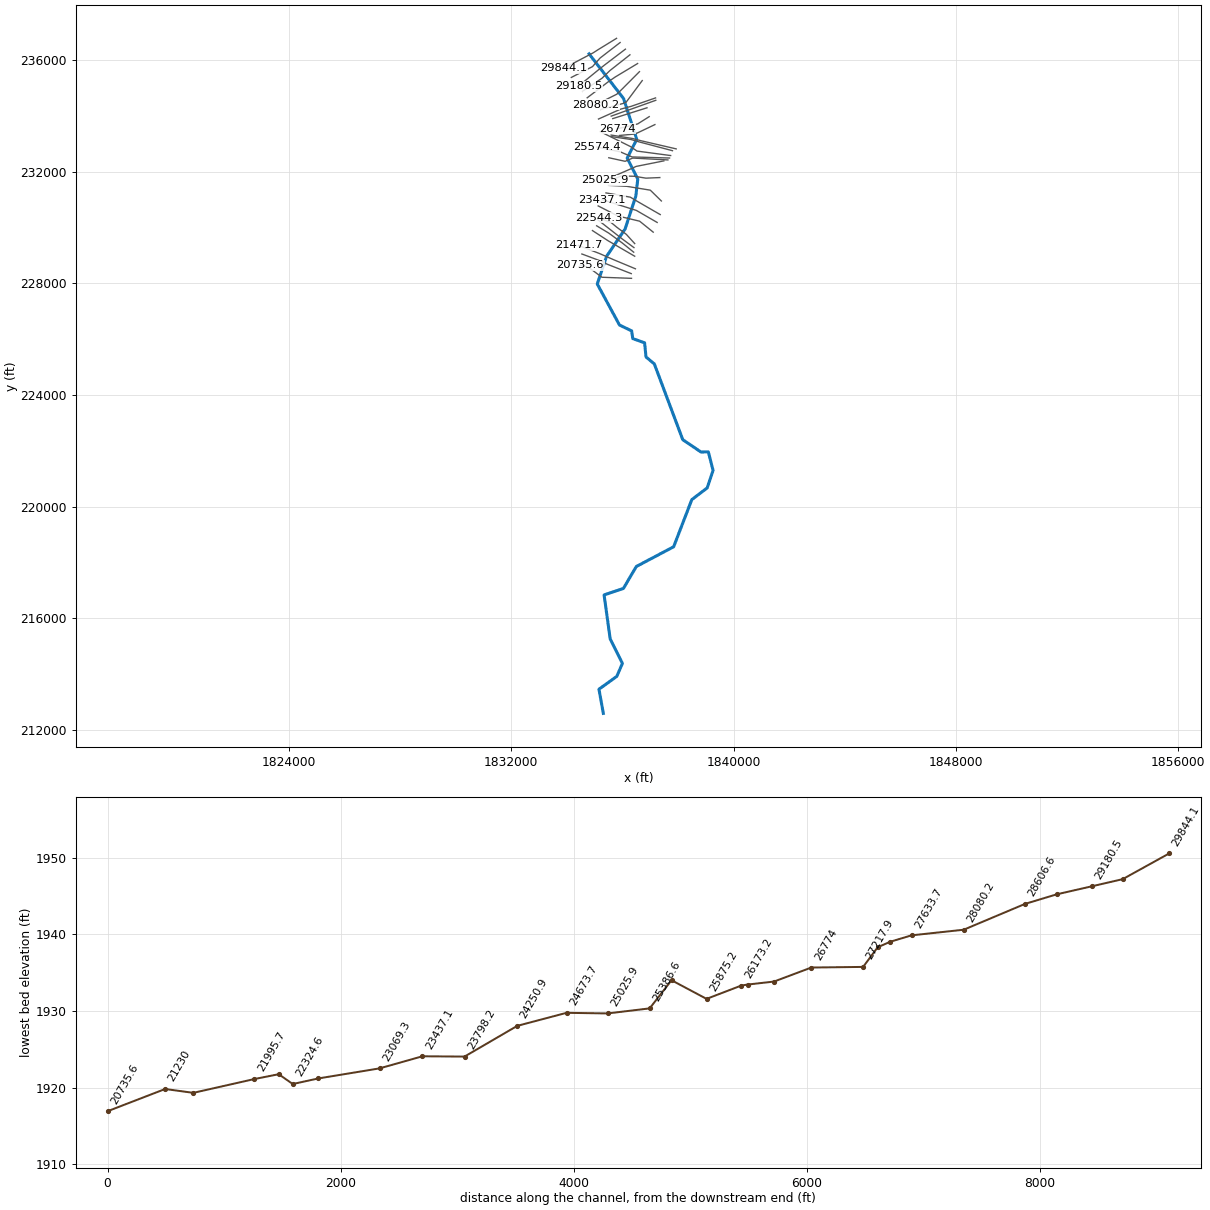
--- CabinCr.prj (project) ---

Proj Title=CabinCr
Current Plan=p01
Default Exp/Contr=0,0
English Units
Geom File=g01
Flow File=f01
Plan File=p01
BEGIN DESCRIPTION:
END DESCRIPTION:
DSS Export Rating Curves= 0
DSS Export Rating Curve Sorted= 0
DSS Export Volume Flow Curves= 0
DXF OffsetX= 0
DXF OffsetY= 0
DXF ScaleX= 0
DXF ScaleY= 0

--- CabinCr.p01 (plan) ---

Plan Title=Floodplain
Program Version=4.00
Geom File=g01
Flow File=f01
K Sum by GR=0
Std Step Tol=0.01
Critical Tol=0.01
Num of Std Step Trials=20
Max Error Tol=0.3
Flow Tol Ratio=0.001
Split Flow NTrial=30
Split Flow Tol=0.02
Split Flow Ratio=0.02
Log Output Level=0
Friction Slope Method=1
Unsteady Friction Slope Method=2
Unsteady Bridges Friction Slope Method=1
Global Log Level=0
CheckData=False
Run HTab=0
Run UNet=0
Run PostProcess=0
UNET Theta=0
UNET Theta Warmup=0
UNET ZTol=0
UNET ZSATol=0
UNET MxIter=0
UNET MaxInSteps=0
UNET DtIC=0
UNET DtMin=0
UNET MaxCRTS=0
UNET WFStab=0
UNET SFStab=0
UNET WFX=0
UNET SFX=0
UNET DSS MLevel=0
UNET DZMax Abort=0
UNET Convert EG Bridges=0
UNET Use Existing IB Tables=0
UNET Froude Limit=0
UNET Froude Power=0
Write IC File=0
Echo Input=False
Echo Output=False
Write Detailed=0

--- CabinCr.f01 (steady flow) ---

Flow Title=NFF Regression Equation
Program Version=4.00
Number of Profiles=1
Profile Names=P100yr
River Rch & RM=CabinCr,Main      ,29844.1
579.4231
River Rch & RM=CabinCr,Main      ,27633.7
630.2125
River Rch & RM=CabinCr,Main      ,27342.7
738.1222
River Rch & RM=CabinCr,Main      ,26228.8
749.7243
River Rch & RM=CabinCr,Main      ,26173.2
886.9287
River Rch & RM=CabinCr,Main      ,25875.2
890.9220
River Rch & RM=CabinCr,Main      ,25574.4
1056.688
River Rch & RM=CabinCr,Main      ,23798.2
1127.769
River Rch & RM=CabinCr,Main      ,21995.7
1233.082
River Rch & RM=CabinCr,Main      ,16275.7
1351.268
River Rch & RM=CabinCr,Main      ,15799.8
1911.398
River Rch & RM=CabinCr,Main      ,11798.3
2088.498
River Rch & RM=CabinCr,Main      ,5199.9
2244.781
River Rch & RM=CabinCr,Main      ,4873.5
2480.897
River Rch & RM=CabinCr,Main      ,2203.3
2641.480
River Rch & RM=CabinCr,Main      ,86.1
2751.352
Boundary for River Rch & Prof#=CabinCr,Main      ,1
Up Type=0
Dn Type=3
Dn Slope=0.016751

--- CabinCr.g01 (geometry) ---

Geom Title=USGS 10m DEM
Program Version=4.00

River Reach=CabinCr         ,Main
Reach XY= 30
     1834800.928      236229.926     1836042.357      234626.228
     1836516.028      233167.692     1836172.757      232492.263
     1836553.448      231741.041     1836483.285       231132.96
     1836096.418      229951.763     1835431.087      228972.456
     1835095.306      227980.066     1835894.575      226509.859
     1836333.604      226299.497     1836372.583      226023.522
      1836798.24      225872.281     1836849.693      225365.547
     1837149.056      225116.078     1838171.619      222400.763
     1838826.475      221957.955     1839092.576      221962.113
     1839262.969      221298.722      1839051.16      220671.393
      1838497.34      220250.266     1837844.469      218561.396
     1836500.102       217853.08      1836035.22      217066.206
     1835340.756      216834.526     1835560.041      215260.283
     1835999.857      214380.651     1835797.527       213915.41
     1835156.357      213454.919     1835313.459      212589.088

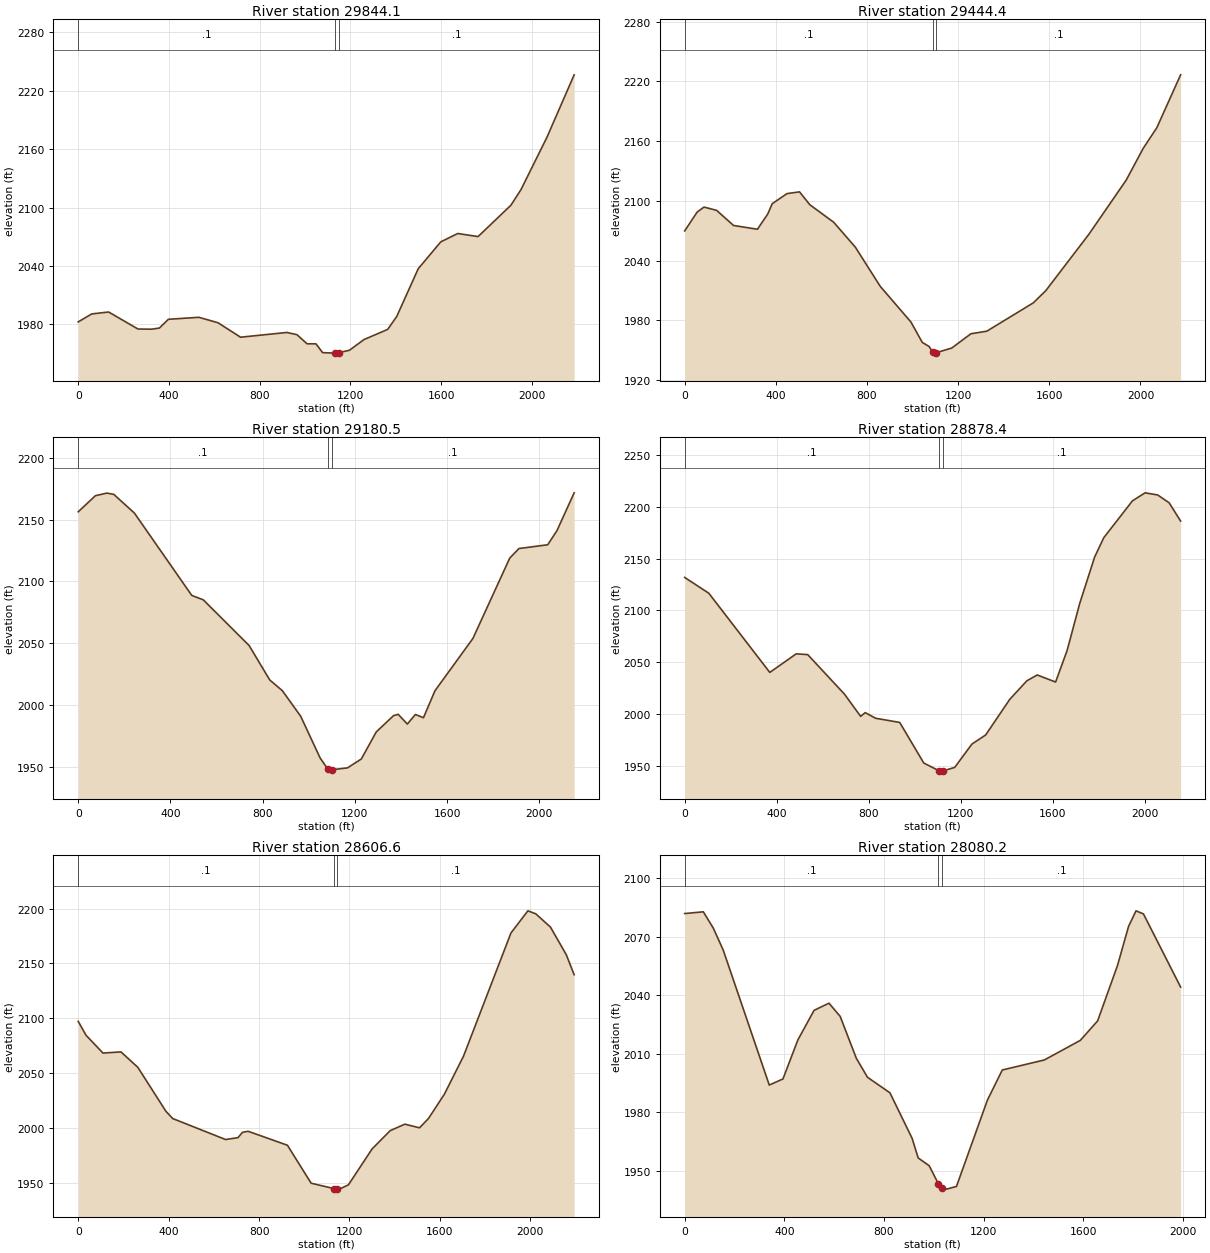
Type RM Length L Ch R = 1 ,29844.1 ,389,399.7,401.4
XS GIS Cut Line= 5
     1835789.509      236786.117     1835132.153       236384.31
     1834947.695      236266.063     1834734.494      236154.498
     1833887.297      235710.073
#Sta/Elev= 30
       0 1982.63    59.6 1990.82   134.2 1992.79   263.4 1975.34   323.1 1975.13
   357.9 1976.31   397.6  1985.3   531.8 1987.36   616.4 1981.78   715.8 1966.91
   919.8 1971.78   964.6 1969.51  1009.2 1960.13  1048.5 1960.11  1077.9 1951.02
  1133.2 1950.63  1136.9 1950.56  1148.2 1951.06  1195.8 1953.46  1260.1 1964.49
  1364.7 1974.93  1404.6 1988.19  1499.2 2037.18  1598.9 2064.86  1673.6 2073.42
  1763.3 2070.26  1907.8 2102.39  1952.7 2118.59  2067.3 2172.42  2186.9 2236.39
#Mann= 3 , 0 , 0
       0      .1       0  1133.2    .045       0  1148.2      .1       0
Bank Sta=1133.2,1148.2
XS Rating Curve= 0 ,0
Exp/Cntr=0.3,0.1

Type RM Length L Ch R = 1 ,29444.4 ,268.1,263.9,259.8
XS GIS Cut Line= 4
     1835917.767      236635.472     1835194.448      236077.732
     1834924.293      235772.718     1834161.758      235384.915
#Sta/Elev= 30
       0 2069.88    54.9 2088.79    84.8 2093.78   139.8 2090.53   214.6 2075.32
   319.4 2071.54   364.4 2086.79   384.3 2097.22   449.2 2107.33   504.1 2109.05
     549 2096.18   653.8 2078.59   748.7 2053.63   858.5 2014.14   992.9 1978.42
  1042.6 1957.99  1072.4  1953.9  1089.8 1947.86  1097.2  1947.2  1104.8  1947.7
  1171.8 1952.29  1256.2 1966.64  1325.8 1969.22  1529.7 1997.64  1584.4 2009.82
  1773.4 2066.38  1937.6 2120.88  2012.2 2152.75  2071.9 2173.44  2176.3 2226.53
#Mann= 3 , 0 , 0
       0      .1       0  1089.8    .045       0  1104.8      .1       0
Bank Sta=1089.8,1104.8
XS Rating Curve= 0 ,0
Exp/Cntr=0.3,0.1

Type RM Length L Ch R = 1 ,29180.5 ,299.6,302.1,304.6
XS GIS Cut Line= 4
     1836108.189      236398.321     1835374.543      235842.455
      1835167.33      235680.803     1834416.137      235069.991
#Sta/Elev= 30
       0 2156.28    74.6 2169.33   124.4 2171.44   154.2 2170.44   243.8 2155.25
   492.6 2088.58   542.3 2085.04   741.3 2048.02   830.9  2020.1   885.6 2011.41
   965.1 1990.74  1049.4 1956.94  1083.8 1947.66    1089 1946.27  1098.8 1947.35
  1168.4 1948.91  1228.2  1956.1    1293 1978.03  1367.9 1991.19  1387.9 1992.32
  1427.8 1984.39  1462.7 1992.15  1497.7 1989.53  1547.6 2011.36  1712.3 2053.74
    1872 2118.79  1911.9 2126.54  2036.7 2129.59  2076.6 2140.95  2151.4 2171.66
#Mann= 3 , 0 , 0
       0      .1       0  1083.8    .045       0  1098.8      .1       0
Bank Sta=1083.8,1098.8
XS Rating Curve= 0 ,0
Exp/Cntr=0.3,0.1

Type RM Length L Ch R = 1 ,28878.4 ,275.4,271.8,268.2
XS GIS Cut Line= 4
     1836270.712       236195.38     1835547.242      235627.557
     1835264.166      235354.413     1834562.634      234888.177
#Sta/Elev= 30
       0 2131.82     105  2116.6   369.9 2040.32   484.8 2058.22   534.8 2057.46
   694.8  2019.3   764.7    1998   784.7 2001.58   829.7 1996.17   934.6 1992.12
  1039.2    1953  1105.9 1945.54  1113.9 1945.22  1120.9 1945.25  1173.6 1948.82
  1248.3 1971.26  1308.1 1980.06  1412.7 2014.33  1487.5 2032.31  1532.4 2037.85
  1612.1 2031.06    1662 2061.37  1716.8 2106.69  1781.6 2151.41  1821.4 2170.09
  1946.1 2205.61  2000.9 2213.34  2055.7 2211.29  2105.6 2203.73  2155.4 2186.15
#Mann= 3 , 0 , 0
       0      .1       0  1105.9    .045       0  1120.9      .1       0
Bank Sta=1105.9,1120.9
XS Rating Curve= 0 ,0
Exp/Cntr=0.3,0.1

Type RM Length L Ch R = 1 ,28606.6 ,522.6,526.4,530.2
XS GIS Cut Line= 4
     1836547.228      235883.058      1835740.43      235399.808
     1835481.206      235220.978      1834732.81      234654.783
#Sta/Elev= 30
       0 2097.11    34.8  2084.4   109.5 2068.18   189.1 2069.23   263.7 2055.16
   388.1 2014.99     418 2008.42   651.8 1989.25   706.6 1990.94   726.5 1995.78
   751.4 1996.79   925.5 1984.03  1030.4 1949.38  1131.8 1944.42  1146.8  1944.3
  1155.4 1943.97  1195.4  1947.9  1300.3 1980.75  1380.2 1997.37  1445.1 2003.27
    1510 1999.94  1549.9 2008.57  1619.8 2030.65  1704.6 2065.44  1914.3 2177.82
  1989.2 2198.02  2024.1 2195.28    2089 2183.17  2158.9    2158  2193.8 2139.72
#Mann= 3 , 0 , 0
       0      .1       0  1131.8    .045       0  1146.8      .1       0
Bank Sta=1131.8,1146.8
XS Rating Curve= 0 ,0
Exp/Cntr=0.3,0.1

Type RM Length L Ch R = 1 ,28080.2 ,454,446.5,438.9
XS GIS Cut Line= 5
     1836613.686       235591.61     1836009.814      234987.738
      1835918.81      234898.373      1835800.43      234784.666
     1835044.116      234407.547
#Sta/Elev= 30
       0 2081.98    74.9 2082.87   114.9 2074.51   154.8 2063.22   339.6 1993.99
   394.5 1997.12   454.5 2017.17   519.4 2032.32   579.3    2036   624.3  2029.2
   689.2 2007.68   734.1 1997.96     824 1990.01   912.9 1966.68   937.4 1956.59
   981.6  1952.6  1018.5 1943.32  1033.5 1941.39  1051.2  1940.6    1091 1941.98
  1215.3 1986.28    1275 2001.72    1444 2006.87  1588.1 2016.91  1657.7 2026.92
  1737.3 2055.28    1782 2075.45  1811.8 2083.38  1841.7 2081.78  1990.8 2044.27
#Mann= 3 , 0 , 0
       0      .1       0  1018.5    .045       0  1033.5      .1       0
Bank Sta=1018.5,1033.5
XS Rating Curve= 0 ,0
Exp/Cntr=0.3,0.1

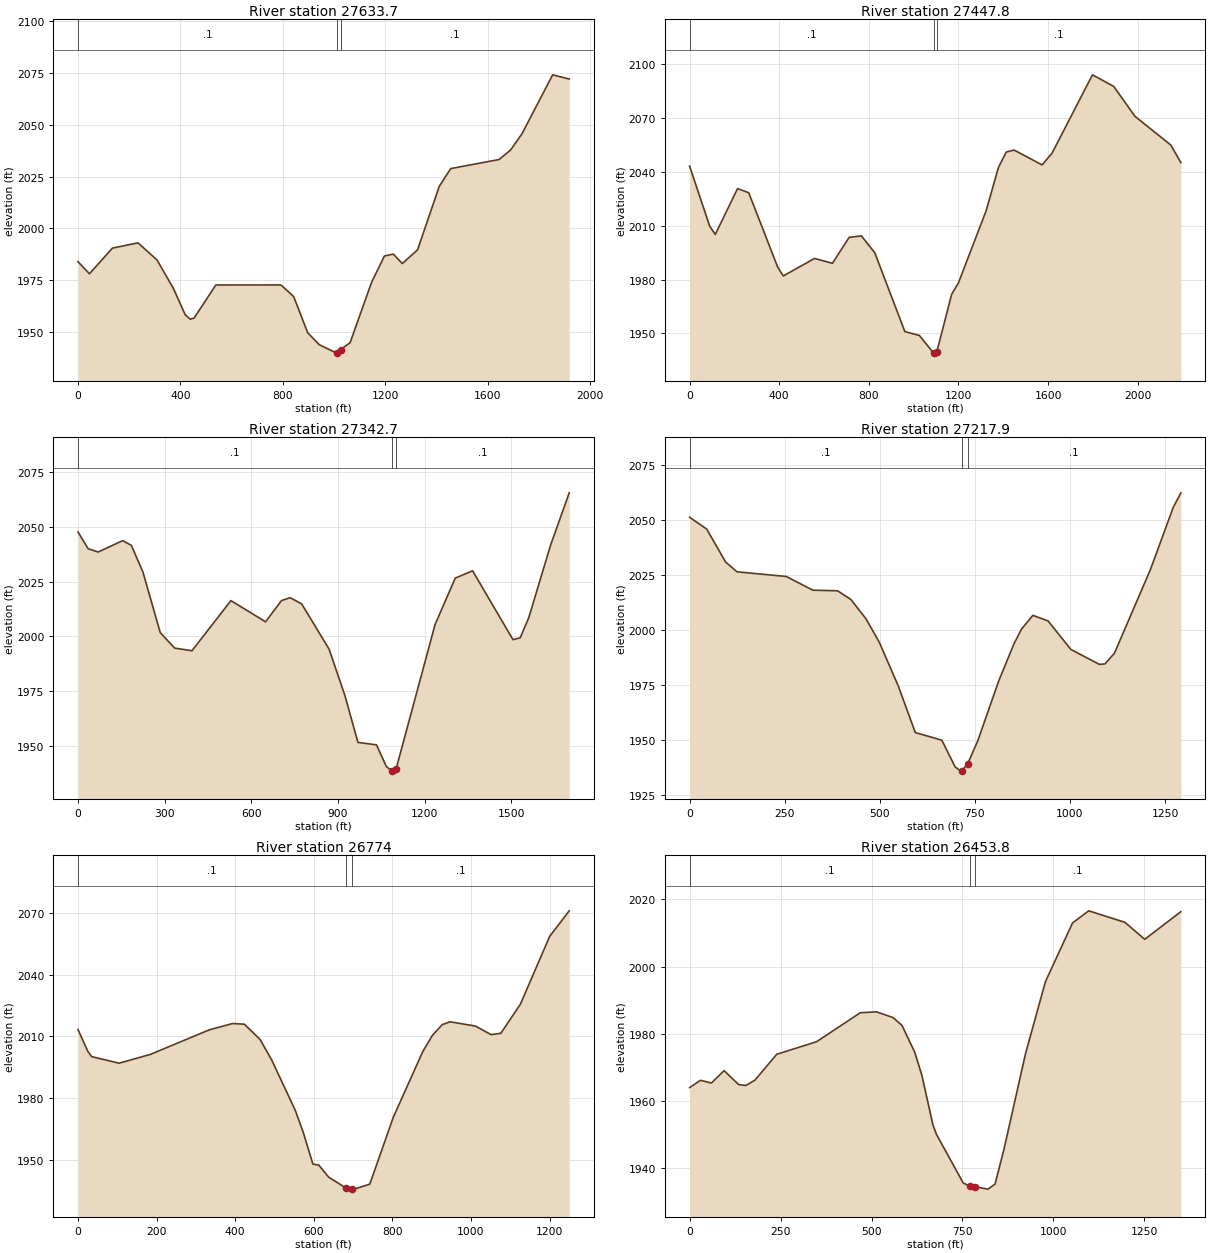
Type RM Length L Ch R = 1 ,27633.7 ,189.5,185.9,182.3
XS GIS Cut Line= 4
     1836714.393      235272.233      1836135.88      234498.224
     1836039.591      234455.716     1835222.083       234238.95
#Sta/Elev= 30
       0 1983.97    44.8 1978.13   134.5 1990.51   234.1 1993.04   308.8 1984.76
   373.6 1970.79   418.4  1958.4   438.3 1956.21   453.3 1956.79     538 1972.73
     792 1972.75   841.8 1967.16   896.6  1949.7   941.4 1943.98  1009.4 1939.87
  1009.8 1939.91  1024.8  1941.6    1062  1944.9  1146.2  1974.1    1196 1986.71
  1230.8 1987.62  1265.6 1983.07  1325.3 1989.66  1409.9 2020.22  1454.6 2028.85
  1643.7 2033.23  1688.5 2037.83  1733.2  2045.7  1852.6 2074.07  1917.3 2072.04
#Mann= 3 , 0 , 0
       0      .1       0  1009.8    .045       0  1024.8      .1       0
Bank Sta=1009.8,1024.8
XS Rating Curve= 0 ,0
Exp/Cntr=0.3,0.1

Type RM Length L Ch R = 1 ,27447.8 ,104.5,105.1,105.8
XS GIS Cut Line= 4
     1837193.294      234650.349     1836303.313        234344.8
     1835933.458      234247.323     1835139.579      233893.961
#Sta/Elev= 30
       0 2043.23    89.6 2009.85   114.5 2005.15   214.1 2030.73   263.9 2028.42
   393.3  1986.9   418.2 1982.04   557.6  1991.8   637.3 1989.08     712 2003.53
   766.7 2004.37   826.5 1994.96   960.8    1951  1025.4 1948.87  1088.6 1939.07
    1090 1939.02  1103.6 1939.89  1169.5 1971.83  1199.3 1978.02  1323.5 2018.38
  1378.4 2042.56  1413.4  2051.1  1448.3  2052.2  1573.2 2043.92  1618.1 2050.59
  1797.9 2094.14  1892.8 2087.69  1987.7 2070.99  2147.5 2055.03  2192.4 2045.22
#Mann= 3 , 0 , 0
       0      .1       0  1088.6    .045       0  1103.6      .1       0
Bank Sta=1088.6,1103.6
XS Rating Curve= 0 ,0
Exp/Cntr=0.3,0.1

Type RM Length L Ch R = 1 ,27342.7 ,124.5,124.9,125.3
XS GIS Cut Line= 4
     1837201.146      234564.858     1836250.623      234225.356
     1836147.698      234195.042     1835597.551      233997.851
#Sta/Elev= 30
       0  2047.8      35 2040.13      70  2038.6   154.9 2043.82   184.9 2041.63
   224.8 2029.48   284.8 2001.73   334.8 1994.62   394.7 1993.41   529.6 2016.36
   649.6 2006.65   704.5 2016.35   734.5  2017.7   774.5 2014.85   869.4 1994.18
   924.4 1972.85   969.4 1951.45  1033.7 1950.33  1067.9  1940.4  1086.8 1938.43
  1092.2 1938.31  1101.8 1939.44  1236.5  2005.4  1306.4 2026.66  1366.4    2030
  1506.2 1998.49  1531.2 1999.31  1561.2 2008.63  1636.1  2041.6    1701 2065.69
#Mann= 3 , 0 , 0
       0      .1       0  1086.8    .045       0  1101.8      .1       0
Bank Sta=1086.8,1101.8
XS Rating Curve= 0 ,0
Exp/Cntr=0.3,0.1

Type RM Length L Ch R = 1 ,27217.9 ,445.1,443.9,442.6
XS GIS Cut Line= 2
     1836884.857      234296.577     1835652.974      233908.438
#Sta/Elev= 30
       0 2051.16    44.9 2045.84    94.8  2030.8   124.7 2026.38   254.3 2024.25
   324.1 2018.03     389 2017.76   423.9 2013.82   463.8    2005   498.7 1994.37
   548.6  1974.5   593.4 1953.29   663.2 1949.82   698.2 1937.64   713.1 1935.75
   715.8 1935.96   730.8 1938.97     758 1949.68   812.8 1976.78   852.7 1993.58
   872.7 2000.35   902.6 2006.58   942.5 2004.06  1002.4 1991.09  1077.2  1984.3
  1092.1  1984.5    1117 1989.36  1211.8 2027.48  1271.6 2055.68  1291.6  2062.3
#Mann= 3 , 0 , 0
       0      .1       0   715.8    .045       0   730.8      .1       0
Bank Sta=715.8,730.8
XS Rating Curve= 0 ,0
Exp/Cntr=0.3,0.1

Type RM Length L Ch R = 1 ,26774   ,319.9,320.2,320.4
XS GIS Cut Line= 4
     1836965.441      233979.184     1836551.919      233719.913
     1836194.191      233628.019     1835810.207      233545.971
#Sta/Elev= 30
       0 2013.32    24.9 2002.76    34.9 2000.11   104.6 1996.92   184.3 2001.19
   333.7 2013.11   393.4 2016.21   423.3 2015.89   463.2 2008.51   493.1 1998.42
     553 1973.96   572.9  1963.5   597.9 1947.83   612.9 1947.36   637.8 1941.49
   681.9 1936.25   696.9 1935.89   702.7 1935.67   742.6 1938.09   802.5 1970.65
   877.3 2002.51   902.2 2010.53     927 2015.68   946.9 2017.05  1011.5 2014.97
  1051.3  2010.8  1076.1 2011.46  1125.8 2025.59  1200.4  2058.6  1250.1 2071.02
#Mann= 3 , 0 , 0
       0      .1       0   681.9    .045       0   696.9      .1       0
Bank Sta=681.9,696.9
XS Rating Curve= 0 ,0
Exp/Cntr=0.3,0.1

Type RM Length L Ch R = 1 ,26453.8 ,236.7,225.1,213.4
XS GIS Cut Line= 4
     1837170.131      233694.448     1836525.893      233388.006
     1836385.279      233350.592     1835896.135      233304.554
#Sta/Elev= 30
       0 1964.03    29.9  1966.2    59.9 1965.39    94.8 1969.08   134.7 1964.94
   154.6 1964.66   179.6 1966.25   239.5 1973.94   349.2 1977.69     469 1986.29
   513.8 1986.56   558.8 1984.87   583.7 1982.54   618.6 1974.61   638.6 1967.62
   668.5 1953.05   678.5 1950.11   752.2 1935.65   770.3 1934.71   785.3 1934.52
   820.1 1933.84   839.5 1935.32   863.9 1945.62   923.4 1974.17     978 1995.52
  1052.5    2013  1097.1  2016.6  1196.4 2013.18    1251 2008.13  1350.2 2016.35
#Mann= 3 , 0 , 0
       0      .1       0   770.3    .045       0   785.3      .1       0
Bank Sta=770.3,785.3
XS Rating Curve= 0 ,0
Exp/Cntr=0.3,0.1

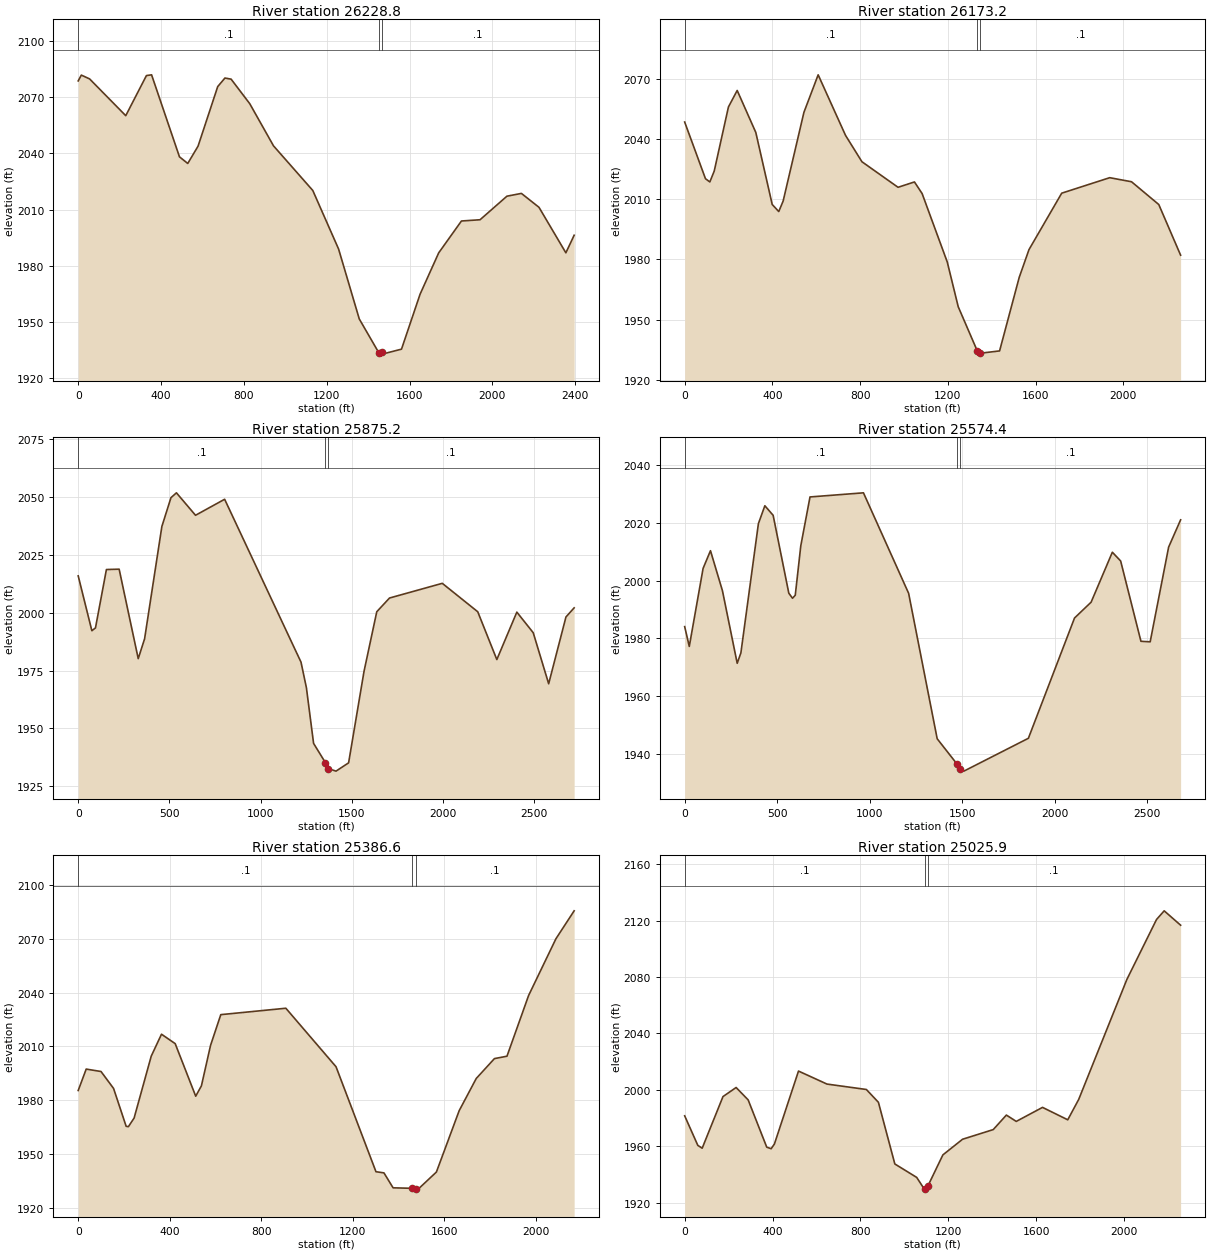
Type RM Length L Ch R = 1 ,26228.8 ,56.3,55.5,54.8
XS GIS Cut Line= 4
     1837935.532      232823.475     1836671.375      233115.429
     1836363.271      233196.037       1835594.1      233319.252
#Sta/Elev= 30
       0 2078.75      15 2081.84    54.9 2079.82   229.6 2060.18   329.4 2081.59
   354.3 2081.99     489 2038.22     529 2034.68   578.8 2043.93   673.7 2075.71
   708.6 2080.28   738.5 2079.67   828.4 2066.58   943.1 2044.08  1132.8 2020.26
  1257.5 1988.98  1357.2  1951.7  1452.4  1933.5  1467.4 1933.79  1486.5 1933.45
  1561.2 1935.57  1650.9  1964.9  1740.7 1986.94  1850.6 2003.97  1940.5 2004.64
  2070.3 2017.21  2140.2  2018.7  2225.1 2011.28  2354.9 1986.99  2394.9 1996.36
#Mann= 3 , 0 , 0
       0      .1       0  1452.4    .045       0  1467.4      .1       0
Bank Sta=1452.4,1467.4
XS Rating Curve= 0 ,0
Exp/Cntr=0.3,0.1

Type RM Length L Ch R = 1 ,26173.2 ,305.4,298.1,290.8
XS GIS Cut Line= 4
     1837801.928      232758.614     1836576.693      233080.568
     1836305.598      233161.142     1835602.006      233263.914
#Sta/Elev= 30
       0 2048.37    94.8 2020.15   114.7 2018.55   134.7 2023.96   199.5 2055.87
   239.4 2064.08   324.2  2043.2     399 2007.33   428.9  2003.8   448.9 2009.05
   543.6  2053.2   608.5 2071.87   733.2 2041.73     808  2028.6   972.6 2015.88
  1047.4 2018.54  1082.3 2012.77    1197 1978.68  1246.9 1956.43  1333.4 1934.53
  1348.4 1933.45  1351.2 1933.32  1435.5 1934.42  1524.8 1970.97  1569.5 1984.85
  1718.7 2012.95  1937.5 2020.66  2036.9 2018.64  2161.2  2007.3  2260.7 1982.08
#Mann= 3 , 0 , 0
       0      .1       0  1333.4    .045       0  1348.4      .1       0
Bank Sta=1333.4,1348.4
XS Rating Curve= 0 ,0
Exp/Cntr=0.3,0.1

Type RM Length L Ch R = 1 ,25875.2 ,296.1,300.7,305.3
XS GIS Cut Line= 4
      1837736.29      232584.673     1836525.257      232744.835
     1836299.171      232902.618     1835202.777      233441.788
#Sta/Elev= 30
       0 2015.93    74.8 1992.23    94.7 1993.46   154.6 2018.67   224.4 2018.83
   329.1 1980.17     364 1988.76   458.7 2037.28   508.6 2049.72   538.5 2051.81
   643.2 2042.11   802.8 2049.03  1221.6 1978.65  1251.1 1967.62  1290.5 1943.56
  1355.8 1935.19  1370.8 1932.66  1413.6 1931.58  1482.5 1935.16  1567.1 1974.71
  1636.9 2000.43  1706.7 2006.36    1996 2012.71  2190.5 2000.44  2295.2 1979.78
  2404.9 2000.27  2494.7 1991.38  2579.4 1969.32  2674.2 1998.18  2719.1 2002.12
#Mann= 3 , 0 , 0
       0      .1       0  1355.8    .045       0  1370.8      .1       0
Bank Sta=1355.8,1370.8
XS Rating Curve= 0 ,0
Exp/Cntr=0.3,0.1

Type RM Length L Ch R = 1 ,25574.4 ,169.2,187.8,206.4
XS GIS Cut Line= 4
     1837696.907      232496.061      1836347.16      232534.367
      1835922.18      232718.432     1835071.695      232891.337
#Sta/Elev= 30
       0 1984.08    24.9 1977.22    99.6 2004.26   139.5 2010.39   204.3 1996.49
     284 1971.38   303.9 1974.97   398.6 2019.76   433.5 2025.96   478.3 2022.65
     563 1995.67     583 1993.91   597.9 1994.96   627.8  2012.1   677.6 2029.01
   966.6 2030.44  1210.8 1995.62  1365.2 1945.23  1473.2  1936.4  1488.2 1934.82
  1509.6 1934.01  1858.3 1945.39  2107.7 1987.06  2197.5 1992.56  2312.2 2009.86
  2357.1 2006.82  2466.8    1979  2516.7 1978.81  2616.5 2011.63  2681.3 2021.08
#Mann= 3 , 0 , 0
       0      .1       0  1473.2    .045       0  1488.2      .1       0
Bank Sta=1473.2,1488.2
XS Rating Curve= 0 ,0
Exp/Cntr=0.3,0.1

Type RM Length L Ch R = 1 ,25386.6 ,360.2,360.7,361.3
XS GIS Cut Line= 4
     1837637.833      232427.141     1836368.592      232494.503
     1836098.591      232378.188     1835510.532      232505.757
#Sta/Elev= 30
       0 1985.37    34.9 1997.32    99.7 1995.96   154.5 1986.52   209.4  1965.4
   219.3  1965.2   244.2 1969.99     319 2004.52   363.9 2016.77   423.7 2011.52
   513.4 1982.19   538.3 1987.97   578.2 2010.55     623 2027.69   907.2 2031.27
  1126.5 1998.61  1300.9 1940.06  1335.8  1939.4  1375.7 1931.07  1460.4 1930.79
  1475.4 1930.47  1485.3 1930.34    1565 1939.88  1664.5 1974.12  1739.1 1992.08
  1818.6 2003.17  1873.3  2004.5  1967.8 2038.37  2087.2 2070.03  2166.8 2085.62
#Mann= 3 , 0 , 0
       0      .1       0  1460.4    .045       0  1475.4      .1       0
Bank Sta=1460.4,1475.4
XS Rating Curve= 0 ,0
Exp/Cntr=0.3,0.1

Type RM Length L Ch R = 1 ,25025.9 ,366.2,352.1,338.3
XS GIS Cut Line= 4
     1837492.577       232393.64     1836495.791      232195.503
     1836305.905      232109.192     1835358.247      231699.561
#Sta/Elev= 30
       0 1981.62    59.8 1960.68    79.7 1958.68   174.4 1995.26   234.1 2001.68
   288.9 1992.92   373.6  1959.4   393.6 1958.32   408.5 1961.67   518.1 2013.33
   647.6 2004.12     827 2000.27   881.8 1991.21   956.5 1947.52    1056 1937.99
  1090.8 1929.68  1091.9 1929.72  1106.9 1931.85  1175.2 1953.92  1264.8 1965.02
  1404.4 1971.86  1464.3 1982.15  1509.2 1977.66  1628.8  1987.6  1743.6  1978.8
  1793.4 1993.23  2012.9 2078.32  2147.6 2120.71  2182.5 2126.87  2257.3 2116.69
#Mann= 3 , 0 , 0
       0      .1       0  1091.9    .045       0  1106.9      .1       0
Bank Sta=1091.9,1106.9
XS Rating Curve= 0 ,0
Exp/Cntr=0.3,0.1

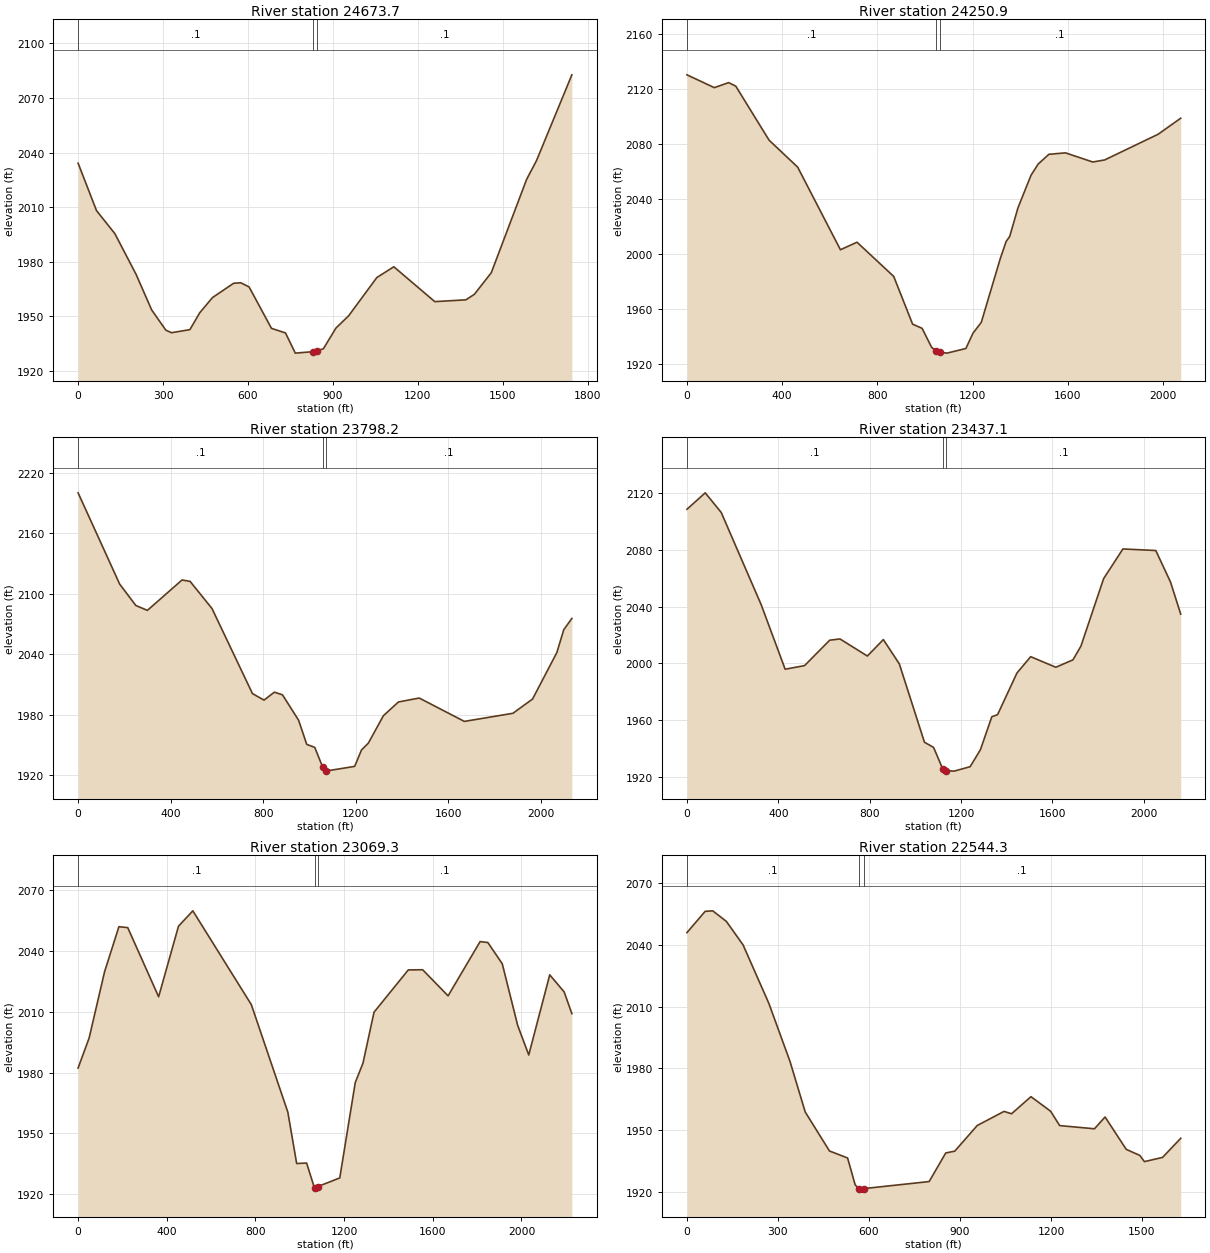
Type RM Length L Ch R = 1 ,24673.7 ,422.4,422.8,423.1
XS GIS Cut Line= 5
     1837347.266      231795.416      1836847.73      231774.282
     1836422.304      231842.235     1835963.244      231853.195
     1835634.439      231720.577
#Sta/Elev= 30
       0 2034.15      65  2008.1     130 1995.39     205 1973.01     260 1953.47
     310 1942.38     330 1940.98     395 1942.67     430    1952     475 1960.31
   549.5 1968.15   574.3 1968.44     604 1966.16   683.2 1943.37   732.7 1940.86
   767.4 1929.76   829.2 1930.55   844.2 1931.16   866.4 1932.11     911 1943.54
   955.8 1950.27  1055.6 1971.33  1115.5 1977.21  1260.2 1958.06    1370 1959.05
    1400 1962.06  1459.9 1973.97  1584.7 2025.26  1619.7  2035.6  1744.5  2082.7
#Mann= 3 , 0 , 0
       0      .1       0   829.2    .045       0   844.2      .1       0
Bank Sta=829.2,844.2
XS Rating Curve= 0 ,0
Exp/Cntr=0.3,0.1

Type RM Length L Ch R = 1 ,24250.9 ,461.6,452.7,442.9
XS GIS Cut Line= 4
     1837402.178       230955.88     1837004.987      231343.494
       1836156.1        231481.5     1835498.468      231516.039
#Sta/Elev= 30
       0 2130.38     115 2121.06     175 2124.71     205 2122.16     345 2082.84
     465 2063.26   644.5 2003.22   714.1 2008.69   868.2 1983.84   947.7  1949.1
   987.5 1946.09  1027.2 1932.39  1045.8 1929.52  1060.8 1928.72  1091.9 1928.06
  1171.4 1931.43  1201.2 1942.54    1236 1950.43  1315.6 1996.67  1340.4 2009.23
  1355.4 2012.87  1390.2 2033.75    1445  2057.4  1474.9 2065.49  1519.8 2072.59
  1589.6 2073.65  1704.4    2067  1754.3 2068.51  1978.8 2087.19  2073.6 2098.85
#Mann= 3 , 0 , 0
       0      .1       0  1045.8    .045       0  1060.8      .1       0
Bank Sta=1045.8,1060.8
XS Rating Curve= 0 ,0
Exp/Cntr=0.3,0.1

Type RM Length L Ch R = 1 ,23798.2 ,355.7,361,366.4
XS GIS Cut Line= 4
     1837361.634      230468.704     1836487.194      230970.809
     1836284.702      231093.083     1835408.065       231245.58
#Sta/Elev= 30
       0 2199.88   179.7 2109.42   249.6 2088.22   299.5 2083.38   449.3 2113.49
   484.2 2112.12     579 2085.16   753.8 2000.91   803.7 1994.44   848.6 2002.32
   883.6 1999.67   953.4 1974.46   988.4 1950.57  1023.1 1947.58  1057.6 1927.92
  1057.6 1927.91  1067.5 1924.05  1072.6 1924.19  1195.6 1928.75  1225.2 1945.01
  1254.9 1951.83  1319.9 1978.97  1384.9 1992.59  1474.8 1996.49  1669.8 1973.34
  1879.8 1981.37  1964.7 1995.48  2069.7 2041.52  2099.7 2064.24  2134.7 2075.37
#Mann= 3 , 0 , 0
       0      .1       0  1057.6    .045       0  1072.6      .1       0
Bank Sta=1057.6,1072.6
XS Rating Curve= 0 ,0
Exp/Cntr=0.3,0.1

Type RM Length L Ch R = 1 ,23437.1 ,366.3,367.8,369.4
XS GIS Cut Line= 4
     1837251.114      230186.605     1836501.651      230617.982
     1835643.254      230888.137     1835264.166      231005.786
#Sta/Elev= 30
       0  2108.7      80  2120.3     150 2106.46   324.9 2041.44   429.9 1995.94
   514.8 1998.48   624.8 2016.39   669.8 2017.29   789.8 2005.24   859.7 2016.83
   929.7  1999.7  1039.7 1944.47  1079.7  1940.8  1120.3 1925.42  1135.3 1924.46
  1169.7 1924.09  1239.7 1927.22  1284.7 1939.18  1334.7 1962.46  1359.7 1963.87
  1444.7 1993.27  1504.7 2004.78  1614.7 1997.33  1689.7 2002.53  1724.6 2012.18
  1824.2 2059.85  1908.5 2080.72  2052.4 2079.63  2116.9  2057.4  2161.6 2034.78
#Mann= 3 , 0 , 0
       0      .1       0  1120.3    .045       0  1135.3      .1       0
Bank Sta=1120.3,1135.3
XS Rating Curve= 0 ,0
Exp/Cntr=0.3,0.1

Type RM Length L Ch R = 1 ,23069.3 ,534.1,525,515.8
XS GIS Cut Line= 4
      1837109.13      229838.885     1836620.156      230231.463
     1835834.613      230419.243     1835128.291       230779.11
#Sta/Elev= 30
       0 1982.22    49.8 1997.03   119.4 2029.68   184.1  2051.9     224 2051.43
   363.3 2017.34   452.9 2052.14   517.6 2059.72   781.6 2013.44   946.2 1960.46
     986 1935.14  1030.9 1935.37  1066.6 1922.96  1070.8 1922.51  1081.6 1923.79
  1180.5 1928.04  1250.3 1975.04  1285.2 1984.62    1335 2009.74  1489.6 2030.59
  1554.4 2030.67  1669.1  2017.8  1813.6 2044.56  1848.6 2044.08  1913.4 2033.64
  1983.2 2003.18    2033 1988.66  2127.7 2028.16  2192.6 2019.76  2227.5 2009.05
#Mann= 3 , 0 , 0
       0      .1       0  1066.6    .045       0  1081.6      .1       0
Bank Sta=1066.6,1081.6
XS Rating Curve= 0 ,0
Exp/Cntr=0.3,0.1

Type RM Length L Ch R = 1 ,22544.3 ,220.2,219.7,219.2
XS GIS Cut Line= 5
     1836442.983      229428.503     1836140.043      229761.005
     1835800.305      230013.382     1835591.483      230185.876
     1835138.121      230354.804
#Sta/Elev= 30
       0    2046      60 2056.34      85 2056.59     130 2051.43   184.9 2040.03
   269.9  2011.6   339.9 1983.22   389.8 1958.74   469.7 1939.77   529.5 1936.35
   554.4 1923.34   567.4 1921.24   569.3  1921.2   582.4 1921.45   798.4 1924.88
   853.1  1938.8   882.9 1939.68   956.8 1952.14  1045.4 1959.02    1070 1957.86
    1134 1966.18  1198.8  1959.1  1228.7 1952.11  1343.4 1950.56  1378.3  1956.3
  1448.1 1940.55    1493 1937.58    1508 1934.58  1567.8 1936.63  1627.7 1945.93
#Mann= 3 , 0 , 0
       0      .1       0   567.4    .045       0   582.4      .1       0
Bank Sta=567.4,582.4
XS Rating Curve= 0 ,0
Exp/Cntr=0.3,0.1

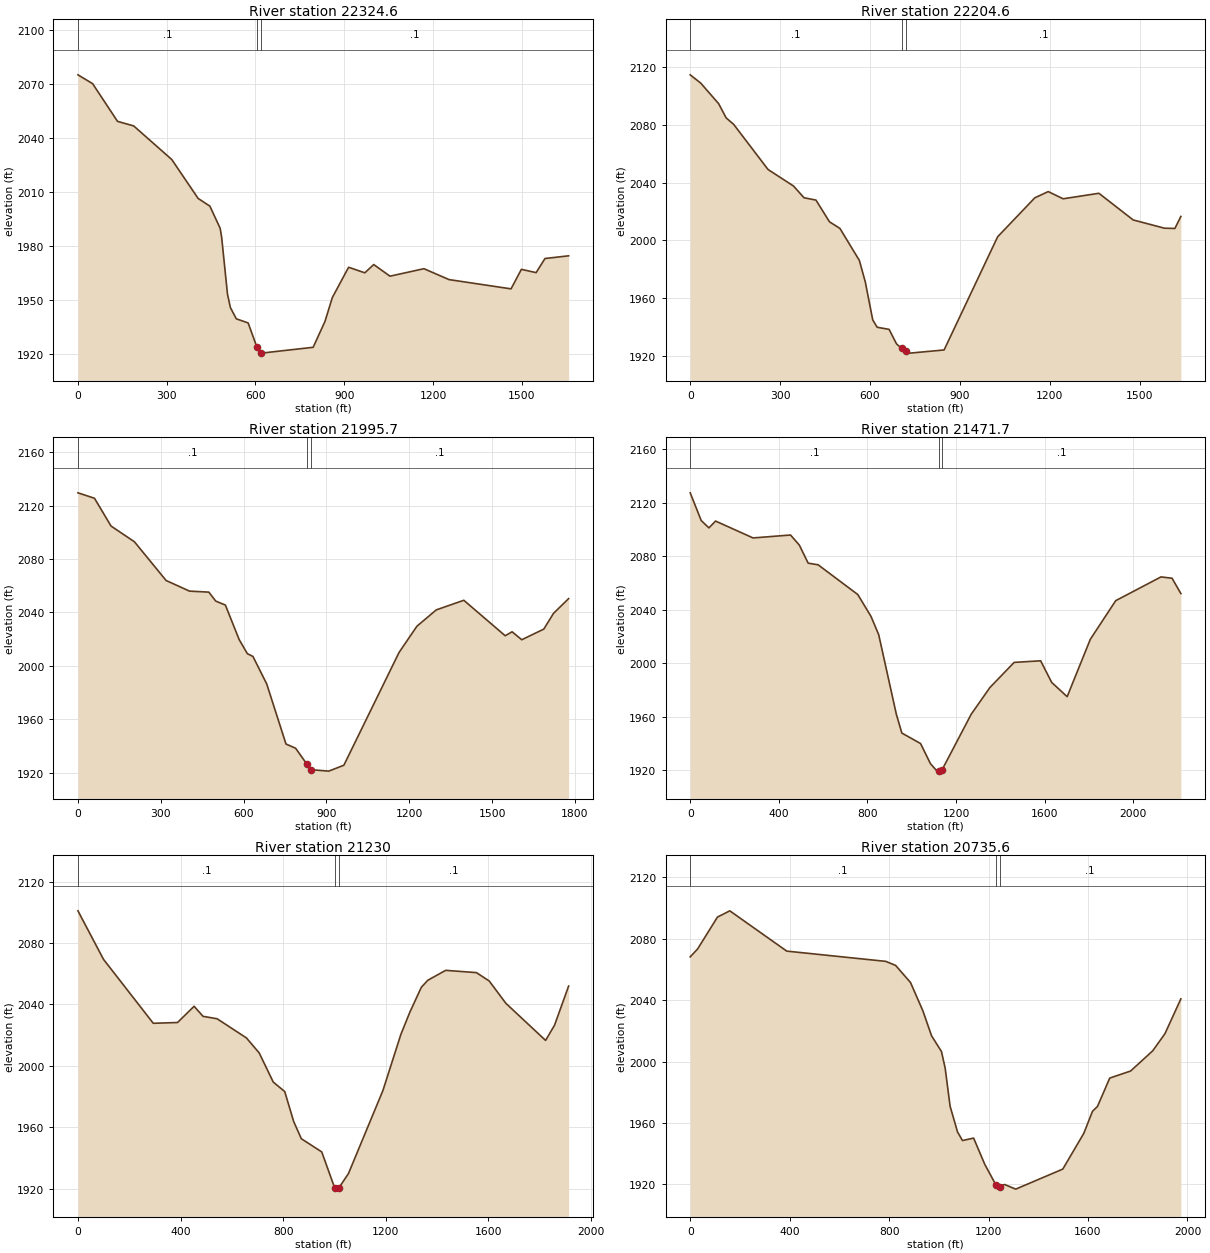
Type RM Length L Ch R = 1 ,22324.6 ,119.2,120,120.8
XS GIS Cut Line= 4
     1836415.585      229284.771       1835992.5      229595.989
      1835437.27      230028.913     1835100.457      230294.576
#Sta/Elev= 30
       0 2075.28    49.6 2070.36   133.8 2049.39   188.3 2046.87   317.1 2028.16
   406.3  2006.5   445.9 2002.24   480.6 1989.92   485.6 1985.02   505.4 1953.26
   515.3  1945.8   535.2 1939.55   575.2 1937.27   605.2 1923.66   620.1 1920.47
   620.2 1920.48   794.9 1923.71   834.8 1938.08   859.8  1951.4   914.7 1968.24
   969.6 1965.14   999.6 1969.75  1054.5 1963.28  1169.4 1967.43  1254.2 1961.37
  1463.7 1956.22  1498.6 1967.08  1548.5 1965.25  1578.4  1973.1  1658.3  1974.6
#Mann= 3 , 0 , 0
       0      .1       0   605.2    .045       0   620.2      .1       0
Bank Sta=605.2,620.2
XS Rating Curve= 0 ,0
Exp/Cntr=0.3,0.1

Type RM Length L Ch R = 1 ,22204.6 ,206.5,208.9,211.2
XS GIS Cut Line= 4
     1836406.505      229120.328      1835989.32      229455.001
     1835511.648      229802.525      1835072.74      230066.945
#Sta/Elev= 30
       0 2114.73      35 2109.02      95 2094.72     120 2084.87     145 2080.41
   259.9 2049.08   344.9 2037.62   379.9  2029.5   419.9 2027.87   464.9 2012.82
   499.8 2008.23   564.6 1986.06   584.5 1971.11   609.3 1944.82   624.2 1939.68
   663.9 1938.23   688.7 1928.18   705.7 1925.03   720.7 1922.93   733.4 1921.75
   847.6 1923.95  1026.3 2002.43  1150.4 2029.44  1195.2 2033.77  1244.9 2028.77
  1364.3 2032.59  1478.8  2014.1  1583.2 2008.38    1618  2008.2    1638 2016.54
#Mann= 3 , 0 , 0
       0      .1       0   705.7    .045       0   720.7      .1       0
Bank Sta=705.7,720.7
XS Rating Curve= 0 ,0
Exp/Cntr=0.3,0.1

Type RM Length L Ch R = 1 ,21995.7 ,521.4,524,526.5
XS GIS Cut Line= 3
     1836442.663      228975.824     1835483.957      229531.151
     1834922.288      229895.323
#Sta/Elev= 30
       0 2129.61    59.9 2125.54   119.8 2104.74   204.6 2092.94   319.4 2063.92
   404.2 2055.97   474.1 2055.22   499.1  2048.5     534 2045.54   583.9  2019.7
   613.8 2009.07   633.8 2007.05   683.7 1986.47   753.6 1941.42   788.5 1938.26
   828.4 1926.61   828.4 1926.59   843.4 1922.21   908.3 1921.12   963.2 1925.54
  1162.9 2009.96  1227.8 2029.68  1297.8  2041.9  1397.7 2049.11  1547.5 2022.55
  1572.5 2025.52  1607.5 2019.54  1687.4 2027.52  1722.4 2039.26  1777.3 2050.37
#Mann= 3 , 0 , 0
       0      .1       0   828.4    .045       0   843.4      .1       0
Bank Sta=828.4,843.4
XS Rating Curve= 0 ,0
Exp/Cntr=0.3,0.1

Type RM Length L Ch R = 1 ,21471.7 ,244.9,241.8,238.6
XS GIS Cut Line= 4
     1836468.265      228525.626     1835691.303      228847.987
     1835176.479      229072.149     1834418.226      229364.011
#Sta/Elev= 30
       0  2127.5    49.8 2106.76    84.6 2101.27   114.5 2106.38   283.7 2093.76
   452.9 2095.94   492.8 2088.39   532.6 2074.87   577.4 2073.68   756.6 2051.42
   816.3 2035.05   851.1 2021.33   930.6 1961.89   955.5  1947.8    1040 1939.96
  1084.7 1924.88  1114.5 1919.32  1121.9 1919.58  1136.9 1920.26  1268.5 1961.85
    1353 1981.85  1462.5 2000.65  1582.1 2001.85    1632 1985.67  1701.8 1975.01
  1806.4 2017.94  1921.1 2046.85  2125.4  2064.6  2175.3 2063.62  2215.2 2052.14
#Mann= 3 , 0 , 0
       0      .1       0  1121.9    .045       0  1136.9      .1       0
Bank Sta=1121.9,1136.9
XS Rating Curve= 0 ,0
Exp/Cntr=0.3,0.1

Type RM Length L Ch R = 1 ,21230   ,496.3,494.3,492.3
XS GIS Cut Line= 4
     1836318.712      228352.044     1835446.977      228691.315
     1835309.392       228770.21     1834542.377      229056.091
#Sta/Elev= 30
       0 2100.92    99.5 2069.38   293.6 2027.74   388.1 2028.24   452.8 2038.81
   487.6 2032.26   542.4 2030.69   656.8  2018.2   706.6 2008.43   761.3 1989.49
   806.1 1983.29   840.9 1963.81   870.7 1952.63   950.3 1944.03  1000.9 1920.55
  1009.8 1919.82  1015.9 1920.34  1054.4 1929.93  1188.9 1984.06  1258.7  2020.5
  1293.7 2034.95  1338.6  2051.2  1363.6 2055.73  1433.4 2062.19  1553.2 2060.71
  1603.1 2055.26    1668 2040.74  1822.8 2016.59  1857.7 2026.49  1912.6 2051.96
#Mann= 3 , 0 , 0
       0      .1       0  1000.9    .045       0  1015.9      .1       0
Bank Sta=1000.9,1015.9
XS Rating Curve= 0 ,0
Exp/Cntr=0.3,0.1

Type RM Length L Ch R = 1 ,20735.6 ,487.5,515.8,544
XS GIS Cut Line= 4
     1836327.879      228183.059     1835263.269      228221.917
     1834786.981      228574.517     1834482.379      228657.591
#Sta/Elev= 30
       0 2068.26    29.9 2073.42   109.5 2094.16   159.3 2098.26   388.3 2072.01
   786.5 2065.33   826.4 2062.67   886.1 2051.56   935.9  2033.1   970.7 2016.86
  1010.6  2006.6  1025.5  1995.8  1045.4 1970.91  1075.3 1954.17  1095.2 1948.58
    1140 1950.17  1184.8 1933.08  1229.2 1919.79  1244.2 1918.41  1264.5 1919.94
  1309.3 1916.92  1498.6 1929.97  1583.2 1953.27  1618.1 1967.64    1638 1970.76
  1687.5 1989.28  1771.4 1993.88  1860.2 2007.02  1909.5  2018.2  1973.6 2040.91
#Mann= 3 , 0 , 0
       0      .1       0  1229.2    .045       0  1244.2      .1       0
Bank Sta=1229.2,1244.2
XS Rating Curve= 0 ,0
Exp/Cntr=0.3,0.1