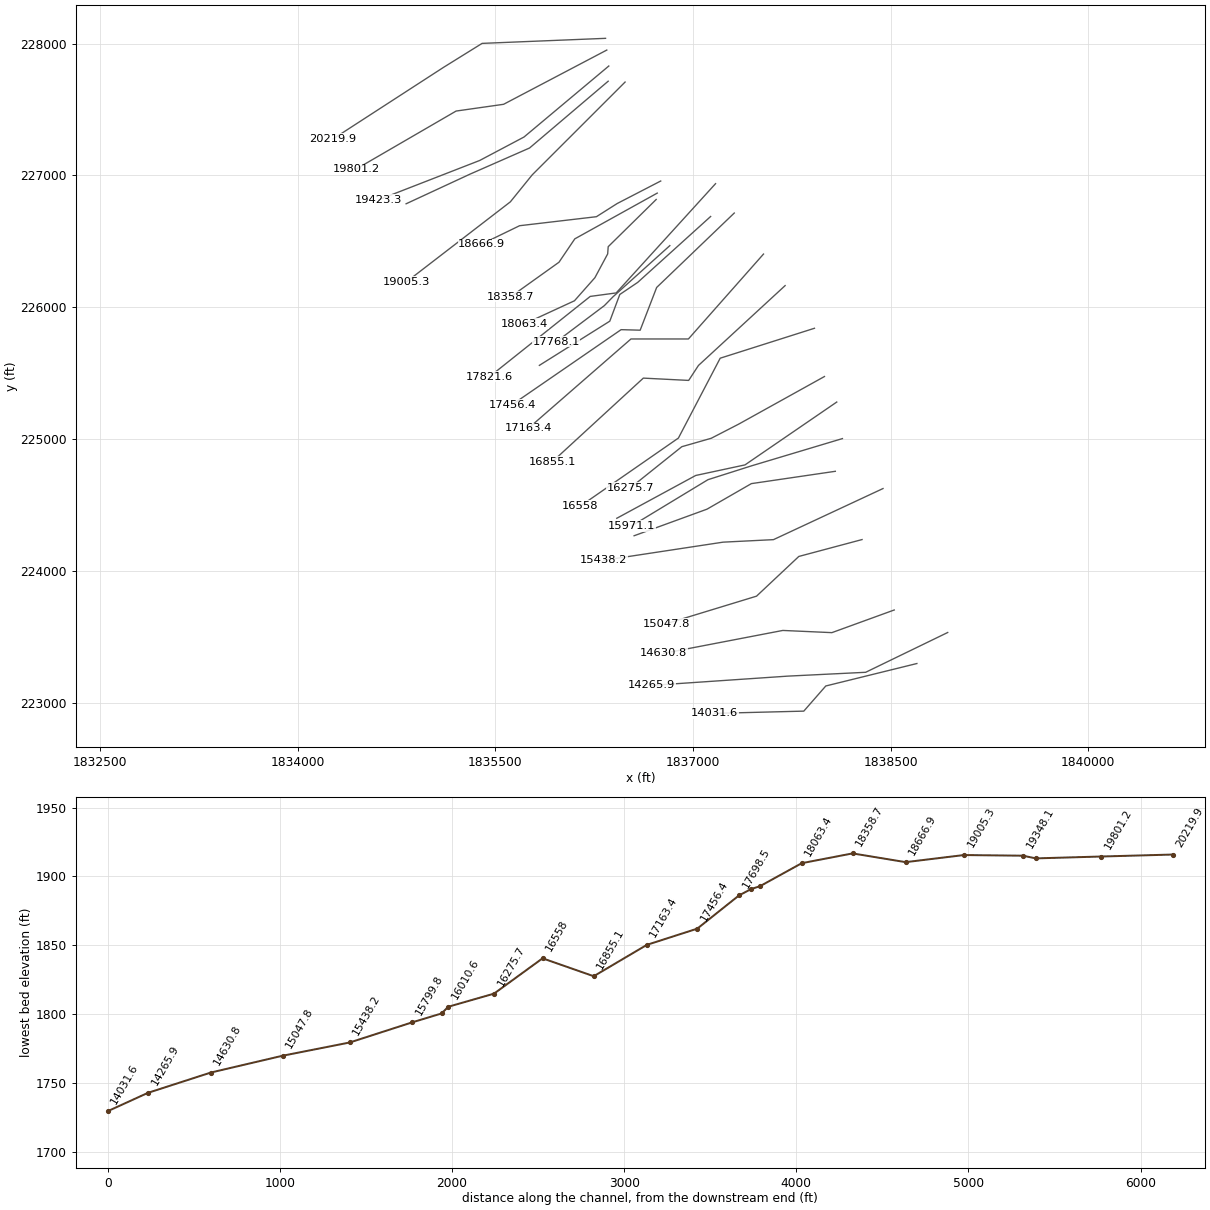
HEC-RAS study CabinCr.prj: CabinCr

--- CabinCr.g01 (geometry) --- (continued)

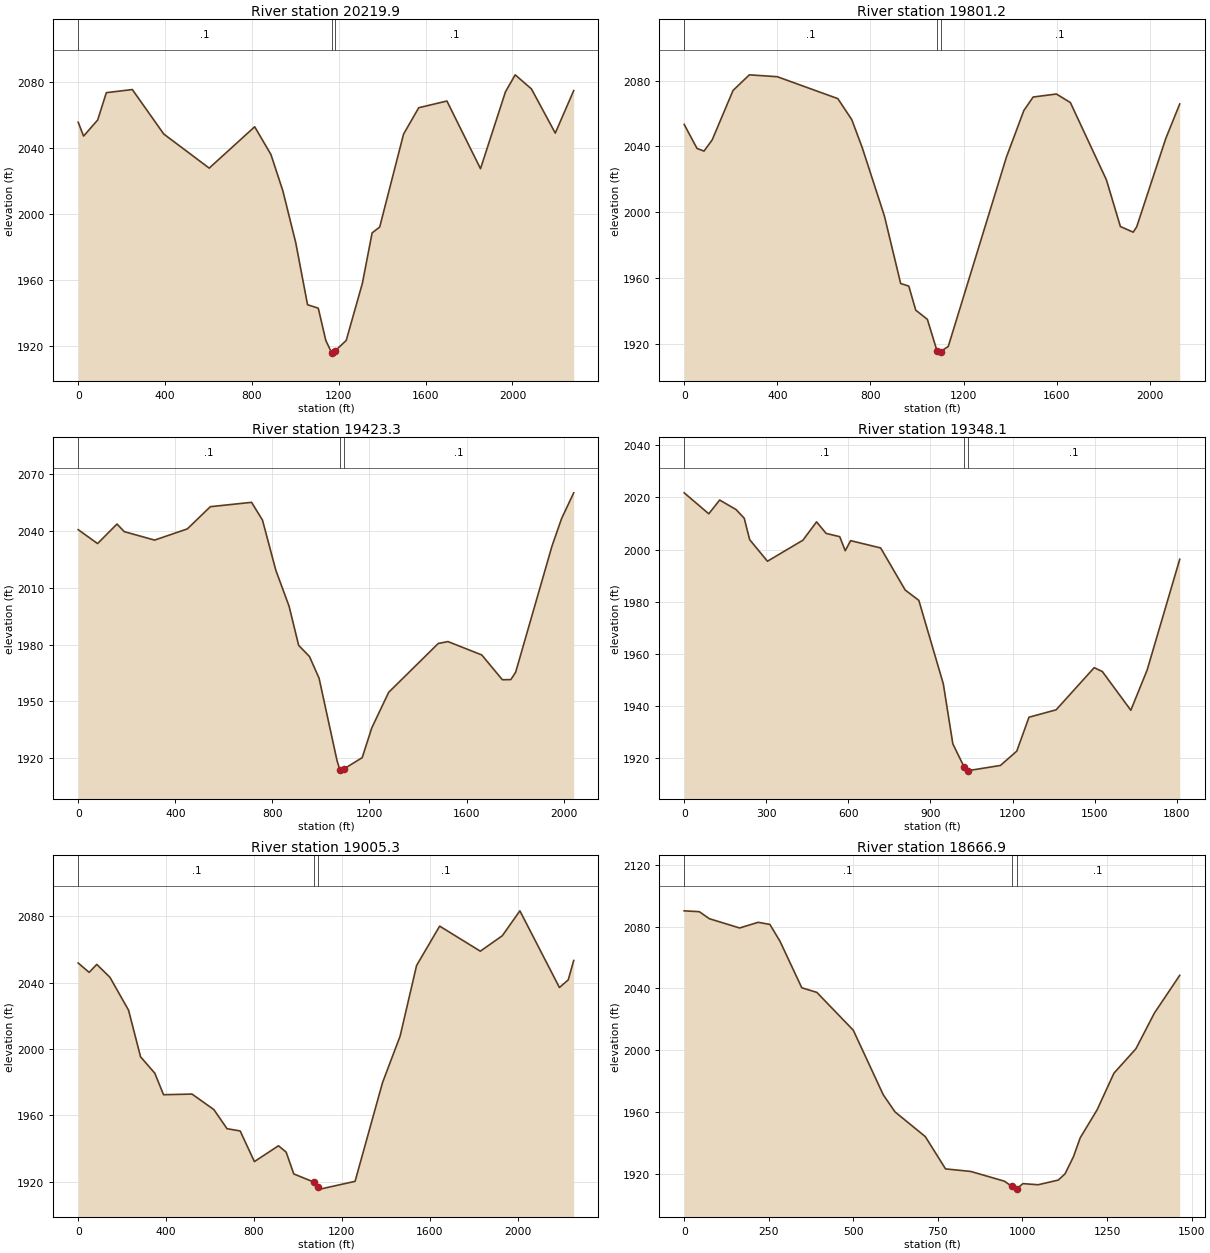
Type RM Length L Ch R = 1 ,20219.9 ,428.3,418.6,409
XS GIS Cut Line= 4
     1836336.969      228039.943     1835400.221      228001.687
     1835105.968      227819.056     1834267.901      227276.605
#Sta/Elev= 30
       0 2055.88    24.9 2047.47    89.8 2057.24   129.7  2073.8   249.3 2075.69
     394 2048.74   603.4 2028.05   812.9 2053.13   887.7 2036.32   942.5 2014.32
  1001.8 1982.99  1056.3 1945.26  1105.7 1943.15  1140.4 1923.61  1166.9 1916.21
  1170.1  1915.9  1181.9 1917.08  1234.4 1923.57  1308.8 1958.18  1353.7 1988.78
  1388.7 1992.36  1498.5 2048.67  1568.4 2064.66  1698.2 2068.73  1852.9  2027.7
  1967.7 2074.25  2012.6 2084.61  2087.5 2076.07  2197.3 2049.28  2282.2 2075.05
#Mann= 3 , 0 , 0
       0      .1       0  1166.9    .045       0  1181.9      .1       0
Bank Sta=1166.9,1181.9
XS Rating Curve= 0 ,0
Exp/Cntr=0.3,0.1

Type RM Length L Ch R = 1 ,19801.2 ,370.2,378,385.7
XS GIS Cut Line= 4
     1836346.369      227951.022     1835563.086      227539.689
      1835202.69      227488.477     1834442.107      227047.265
#Sta/Elev= 30
       0 2053.37      55 2038.79      85 2037.17     120 2043.92   209.9 2074.03
   279.9 2083.49   399.9 2082.34   659.8 2069.03   719.8 2056.23   764.8 2039.17
   859.7 1997.81   929.6 1956.76   964.5 1955.17   994.4 1940.56  1044.3 1934.98
  1085.8  1915.8  1094.2 1914.46  1100.8 1915.39    1134 1918.51  1383.6 2033.45
  1458.6  2061.8  1498.5 2070.01  1598.4 2071.84  1658.4 2066.65  1813.3 2019.66
  1873.2 1991.36  1928.2 1987.92  1943.2 1991.17  2068.1 2044.82    2128 2065.78
#Mann= 3 , 0 , 0
       0      .1       0  1085.8    .045       0  1100.8      .1       0
Bank Sta=1085.8,1100.8
XS Rating Curve= 0 ,0
Exp/Cntr=0.3,0.1

Type RM Length L Ch R = 1 ,19423.3 ,76.8,75.2,73.5
XS GIS Cut Line= 4
     1836361.627      227829.998      1835717.87      227291.446
      1835381.76      227113.724     1834615.469      226815.886
#Sta/Elev= 30
       0 2040.66    79.9 2033.32   159.9 2043.64   189.8 2039.62   314.8 2035.15
   449.6 2041.06   544.6  2052.8   714.4  2055.1   759.4  2045.7   814.3 2019.23
     869  2000.2   908.4 1979.54   952.9 1973.66   992.4 1962.25  1066.5 1918.67
    1079 1913.45  1081.3 1913.11    1094  1914.2  1170.2 1920.24  1209.6 1935.94
  1279.3 1954.74  1483.6 1980.54  1523.5 1981.55    1663 1974.47  1747.7 1961.39
  1782.6 1961.46  1802.5 1965.36    1952  2031.9  1991.8 2046.57  2041.7 2060.12
#Mann= 3 , 0 , 0
       0      .1       0    1079    .045       0    1094      .1       0
Bank Sta=1079,1094
XS Rating Curve= 0 ,0
Exp/Cntr=0.3,0.1

Type RM Length L Ch R = 1 ,19348.1 ,363.2,342.7,354.3
XS GIS Cut Line= 4
     1836356.994      227714.829     1835760.116      227208.281
     1835309.501      227010.642     1834823.312      226785.335
#Sta/Elev= 30
       0 2021.77    89.8 2013.73   129.6 2019.01   189.5 2015.36   219.4 2012.03
   239.3  2003.8   304.2 1995.54   433.8  2003.6   483.7 2010.64   518.6 2006.21
   568.4 2004.96   588.4 1999.58   608.3 2003.43     718 2000.63   807.7 1984.48
   857.4 1980.54   946.9 1948.51   981.7 1925.51  1023.7  1916.5  1036.3 1915.06
  1038.7 1915.26  1155.6 1917.24  1215.3 1922.72    1260 1935.73  1359.2 1938.57
  1498.2 1954.73    1528 1953.25  1632.1  1938.4  1691.7 1953.81  1810.8 1996.28
#Mann= 3 , 0 , 0
       0      .1       0  1023.7    .045       0  1038.7      .1       0
Bank Sta=1023.7,1038.7
XS Rating Curve= 0 ,0
Exp/Cntr=0.3,0.1

Type RM Length L Ch R = 1 ,19005.3 ,355.1,338.4,321.2
XS GIS Cut Line= 4
     1836485.249      227708.481     1835780.513      227004.805
     1835614.366      226799.891     1834825.927      226193.275
#Sta/Elev= 30
       0 2051.89    49.8 2046.24    84.6 2051.03   144.4 2043.28   229.1 2023.45
   283.8 1995.32   348.6 1985.43   388.4 1972.46   517.9 1972.85   617.5 1963.48
   677.2 1951.97     737 1950.61   801.7 1932.12   911.2 1941.68   946.1 1937.86
     981 1924.68  1074.9 1919.64  1089.9 1916.68  1100.4 1915.53  1259.7 1920.22
  1384.7 1979.77  1464.7  2007.8  1539.6 2050.38  1644.6 2074.13  1829.6 2059.01
  1929.6 2068.33  2009.6 2083.35  2189.5 2037.11  2229.5 2041.69  2254.5  2053.4
#Mann= 3 , 0 , 0
       0      .1       0  1074.9    .045       0  1089.9      .1       0
Bank Sta=1074.9,1089.9
XS Rating Curve= 0 ,0
Exp/Cntr=0.3,0.1

Type RM Length L Ch R = 1 ,18666.9 ,288.5,308.2,327.9
XS GIS Cut Line= 5
     1836755.702      226957.977     1836424.793      226786.968
     1836267.658      226687.302     1835684.517      226618.975
     1835397.392      226479.744
#Sta/Elev= 30
       0 2090.17    44.7 2089.61    74.5 2085.07   163.9 2079.09   218.5 2082.74
   253.3  2081.4   283.1 2070.54   347.6 2040.46   392.1 2037.49   499.8 2013.06
   588.4 1971.35   623.2 1960.28   712.8  1944.3   772.5 1923.45   847.2  1921.8
   946.7  1915.5     968 1912.25   981.5 1910.38     983  1910.7  1001.4 1913.94
  1046.2  1913.2  1105.9 1916.23  1125.8 1920.27  1150.7 1931.33  1170.6 1943.52
  1220.5 1961.57  1270.3 1985.27  1335.2 2001.03    1390 2024.14  1464.8 2048.49
#Mann= 3 , 0 , 0
       0      .1       0     968    .045       0     983      .1       0
Bank Sta=968,983
XS Rating Curve= 0 ,0
Exp/Cntr=0.3,0.1

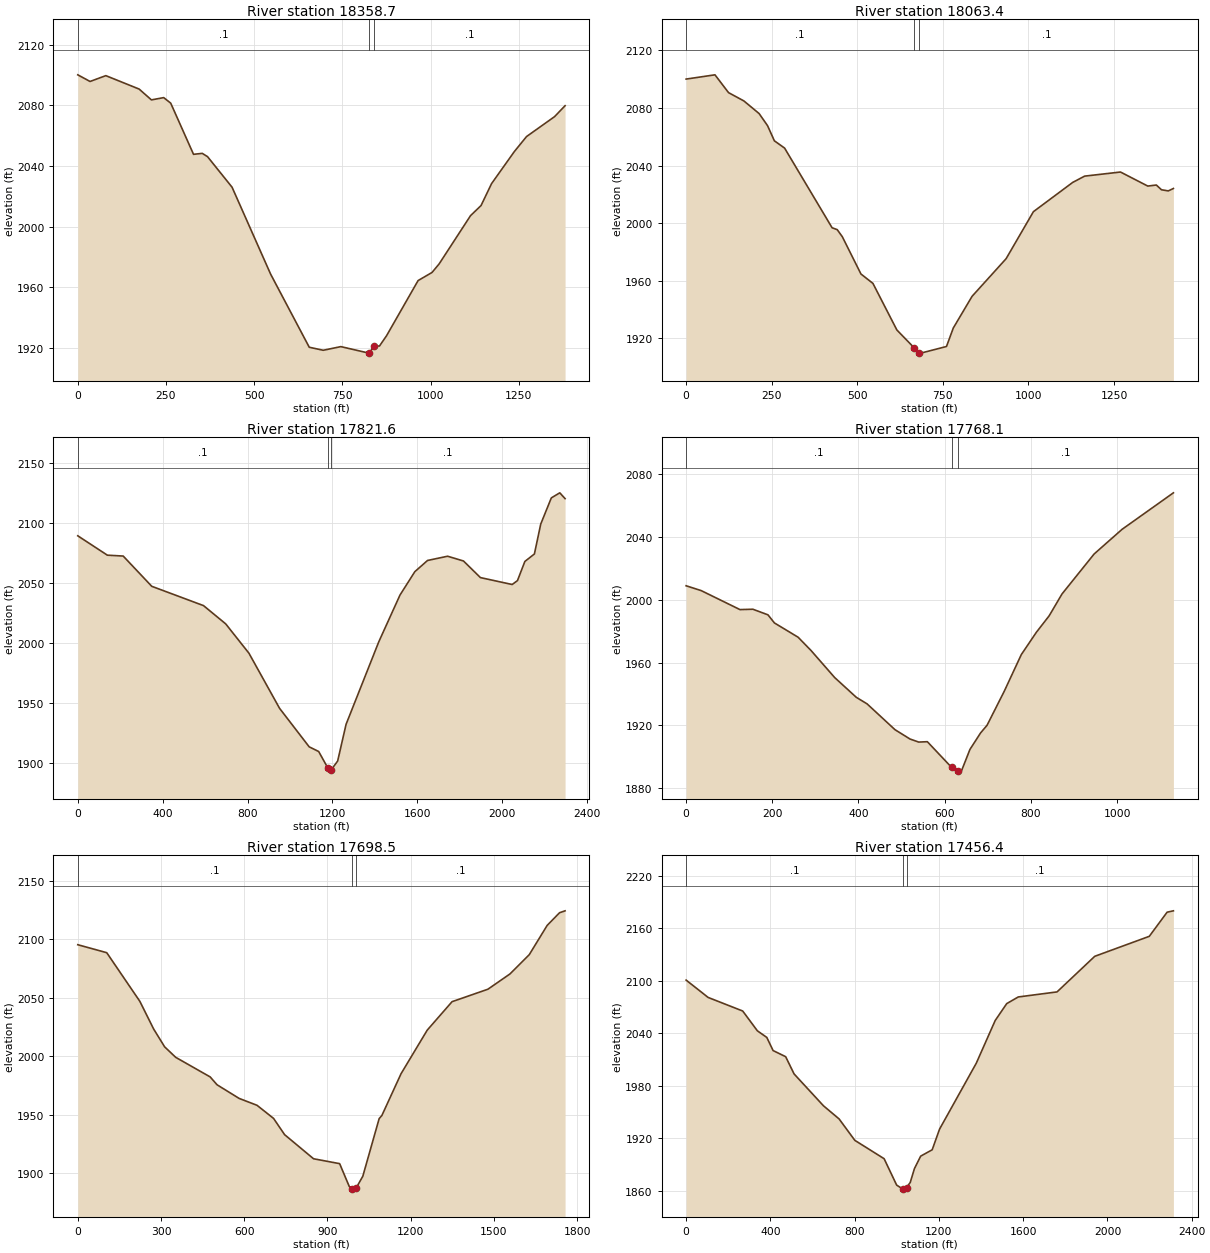
Type RM Length L Ch R = 1 ,18358.7 ,293.2,295.3,297.4
XS GIS Cut Line= 4
     1836729.396      226866.349     1836103.576      226519.287
     1835983.581      226342.063     1835616.212      226079.921
#Sta/Elev= 30
       0  2100.2    34.8 2095.82    79.5 2099.66   173.9 2090.81   208.7 2083.67
   243.5 2085.18   263.4 2081.52     328 2047.79   352.8 2048.42   367.8 2046.24
   437.3 2026.08   546.6 1968.77     656  1920.6   695.7  1918.6   745.5 1921.01
   825.1 1916.72   825.3 1916.78   840.3 1921.35     855  1921.4   874.9 1928.12
   964.4 1964.54    1004 1969.92  1023.9 1975.48  1113.1 2007.36  1142.9 2014.03
  1172.6 2028.45  1237.1 2049.57  1271.8  2059.5  1351.2 2072.63    1381 2079.84
#Mann= 3 , 0 , 0
       0      .1       0   825.3    .045       0   840.3      .1       0
Bank Sta=825.3,840.3
XS Rating Curve= 0 ,0
Exp/Cntr=0.3,0.1

Type RM Length L Ch R = 1 ,18063.4 ,263.9,241.8,219.9
XS GIS Cut Line= 6
     1836721.383      226817.904     1836357.134       226459.93
     1836353.088      226405.137      1836256.12      226224.733
     1836100.921      226049.684     1835720.491      225874.264
#Sta/Elev= 30
       0  2100.1    84.3 2103.06     124 2090.67   168.6 2084.94   213.2 2076.14
     238 2067.68   257.8 2057.19   287.6 2052.16   426.4 1996.76   441.3 1995.47
   456.2 1990.56   510.7 1964.62   545.7 1958.09   615.6 1925.72   666.6  1913.2
   681.6 1909.94   685.5 1909.63   760.5 1914.24   780.4 1927.08   835.2  1949.1
   934.7 1975.28  1014.4 2007.94  1129.1 2028.27    1164 2032.65  1268.7  2035.5
  1348.5 2025.74  1373.5 2026.47  1388.4 2023.17  1408.4 2022.39  1423.3 2024.06
#Mann= 3 , 0 , 0
       0      .1       0   666.6    .045       0   681.6      .1       0
Bank Sta=666.6,681.6
XS Rating Curve= 0 ,0
Exp/Cntr=0.3,0.1

Type RM Length L Ch R = 1 ,17821.6 ,37.7,53.5,69.1
XS GIS Cut Line= 4
      1837171.86      226937.917     1836417.658      226109.303
     1836220.687      226082.855     1835456.047      225473.854
#Sta/Elev= 30
       0 2089.54   139.4 2073.36   214.1 2072.62   348.6 2047.36   592.6 2031.23
   697.2 2015.97   806.7 1991.46   951.1 1945.42  1090.6 1913.28  1135.4 1909.35
  1177.3 1895.99    1190 1892.97  1192.3 1893.53  1224.8 1901.39  1264.5 1932.06
  1418.9 2001.09  1518.7 2040.07  1588.5 2059.56  1648.4 2068.93  1743.1 2072.48
  1817.9  2068.5  1897.7 2054.64  2047.4 2048.85  2072.3 2052.13  2107.2 2068.12
  2152.1 2074.36    2182 2099.34  2231.9  2121.2  2271.8 2125.44  2296.7 2120.61
#Mann= 3 , 0 , 0
       0      .1       0  1177.3    .045       0  1192.3      .1       0
Bank Sta=1177.3,1192.3
XS Rating Curve= 0 ,0
Exp/Cntr=0.3,0.1

Type RM Length L Ch R = 1 ,17768.1 ,58.8,69.6,80
XS GIS Cut Line= 4
     1836824.694      226467.857     1836393.659      226080.065
     1836328.097      226013.108     1835962.624      225738.306
#Sta/Elev= 30
       0 2008.94      35 2005.86     125 1993.75     155 1993.98   189.9 1990.42
   204.9 1985.25   259.9 1976.14   289.9 1967.67   344.9 1950.39   394.9 1937.84
   419.9 1933.66   484.8 1917.18   519.8 1911.22   539.8  1909.3   559.8 1909.54
     616 1893.19     631 1891.02   634.1 1890.78     639 1890.92   658.7 1904.64
   683.5 1915.19   698.4 1920.03   738.1  1941.6   777.9 1965.09   812.7 1979.26
   842.5  1989.8   872.3 2003.72   946.9 2029.22  1011.5 2044.88  1130.8 2068.19
#Mann= 3 , 0 , 0
       0      .1       0     616    .045       0     631      .1       0
Bank Sta=616,631
XS Rating Curve= 0 ,0
Exp/Cntr=0.3,0.1

Type RM Length L Ch R = 1 ,17698.5 ,242.4,242.1,241.9
XS GIS Cut Line= 5
     1837134.492      226688.888     1836581.105      226189.258
      1836445.13      226097.554     1836369.237      225895.173
     1835834.824      225559.978
#Sta/Elev= 30
       0 2095.36   104.4 2088.53   223.7 2046.92   273.4 2023.25   313.1 2007.96
   352.9 1998.99   477.2 1982.22     502  1975.5   581.5 1963.83   646.2 1957.91
   705.8  1946.7   745.6 1932.79   849.9 1912.17     944 1907.98   978.4 1888.57
   988.2 1886.18   989.4  1886.2  1004.4 1887.52  1027.5 1897.22  1086.4 1946.52
  1096.2  1949.2  1165.4 1984.99  1259.8 2022.28  1349.2  2046.6  1478.4 2057.26
  1557.9 2070.33  1627.4 2086.81    1692 2111.87  1736.7 2122.74  1756.6 2124.36
#Mann= 3 , 0 , 0
       0      .1       0   989.4    .045       0  1004.4      .1       0
Bank Sta=989.4,1004.4
XS Rating Curve= 0 ,0
Exp/Cntr=0.3,0.1

Type RM Length L Ch R = 1 ,17456.4 ,325.7,293,266
XS GIS Cut Line= 5
     1837313.836      226715.091     1836724.812       226150.61
     1836599.756       225826.65      1836455.03      225830.775
     1835626.715      225261.309
#Sta/Elev= 30
       0 2100.79   104.5 2080.98   268.6 2065.49   338.3 2042.88     383 2035.33
   412.9 2020.32   472.6 2013.32   512.4 1993.68   651.7 1957.33   726.3 1942.23
   800.9  1917.8   939.9 1896.84   999.4  1866.7  1029.2  1862.1  1031.2 1862.16
  1046.2 1863.94  1063.9 1869.69  1083.7 1885.46  1113.5 1899.76  1168.1 1907.04
    1203 1930.58  1377.6 2005.99  1467.1 2054.62  1521.9 2073.93  1576.6 2081.52
  1760.7  2087.3  1939.8 2127.95  2198.6 2150.76  2283.2 2178.32  2313.1 2179.88
#Mann= 3 , 0 , 0
       0      .1       0  1031.2    .045       0  1046.2      .1       0
Bank Sta=1031.2,1046.2
XS Rating Curve= 0 ,0
Exp/Cntr=0.3,0.1

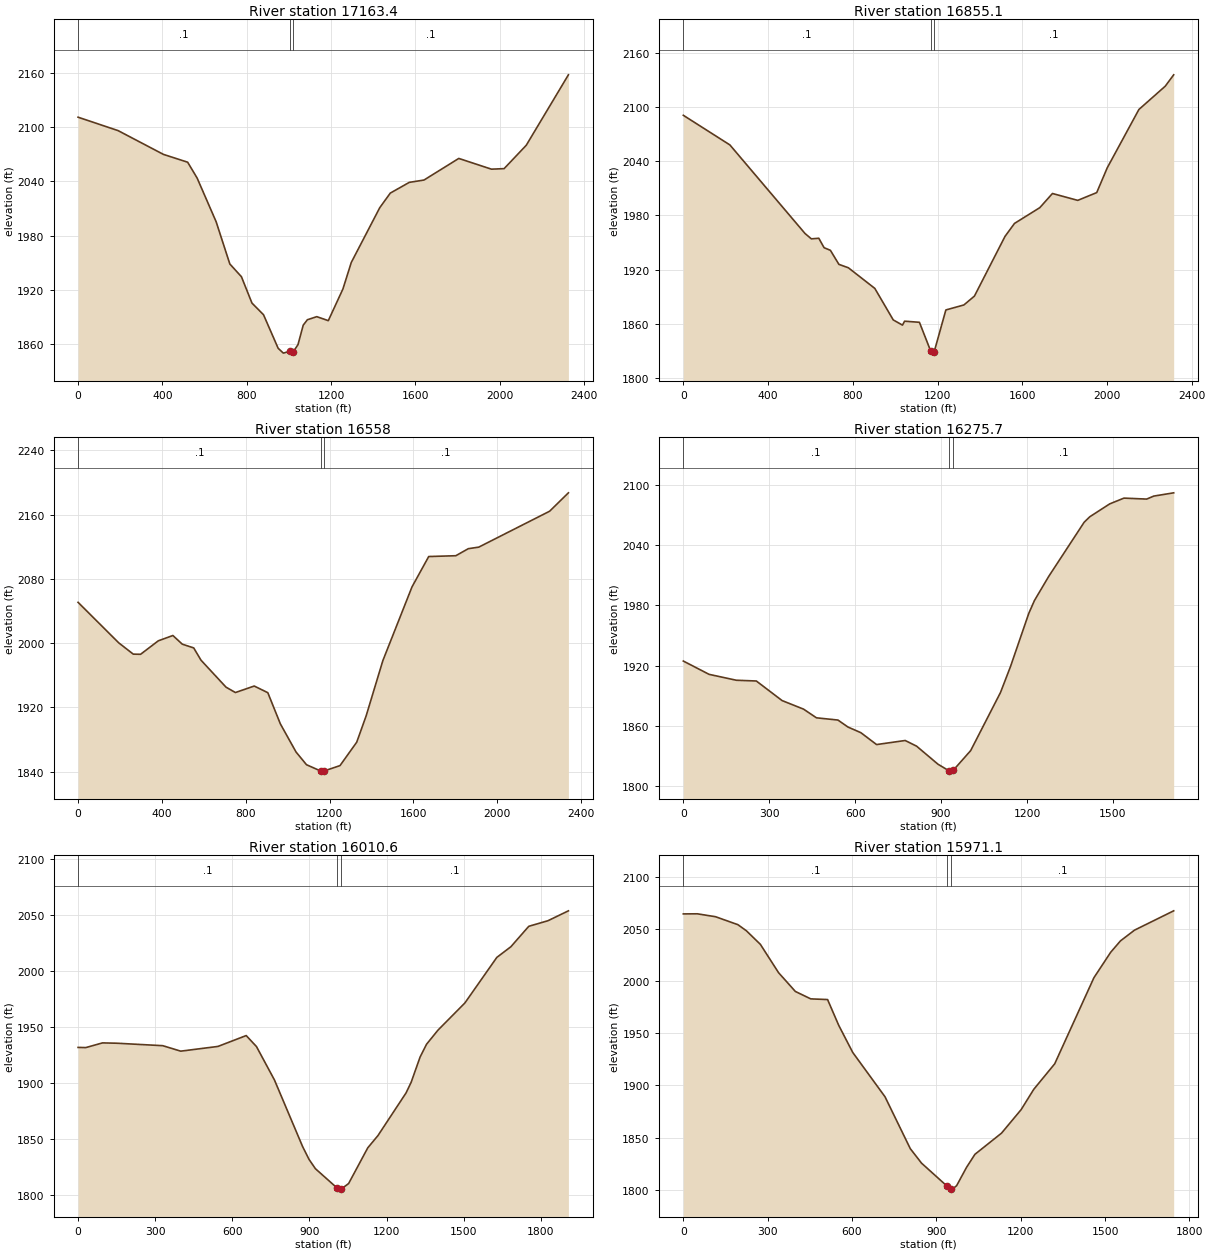
Type RM Length L Ch R = 1 ,17163.4 ,309.6,308.3,307.2
XS GIS Cut Line= 4
     1837535.799      226403.979     1836965.921      225760.092
     1836529.786      225760.092     1835752.929      225083.983
#Sta/Elev= 30
       0 2111.03     190 2096.18   404.9 2069.92   519.9 2061.28   564.9 2043.73
   654.9 1995.53   719.9 1948.84   774.9 1934.76   824.9 1905.62   879.7 1892.75
   949.1 1855.68   973.8 1850.33  1005.3 1852.43  1020.3 1851.64  1043.2 1859.71
    1068 1881.22  1087.8 1887.22  1132.4 1890.62    1187 1886.21  1256.3 1921.19
    1296 1950.52    1431 2011.01    1481 2027.14    1571 2038.99    1641 2041.59
  1805.9 2065.45  1960.9 2053.59  2020.9 2054.18  2125.9 2079.98  2325.9 2157.83
#Mann= 3 , 0 , 0
       0      .1       0  1005.3    .045       0  1020.3      .1       0
Bank Sta=1005.3,1020.3
XS Rating Curve= 0 ,0
Exp/Cntr=0.3,0.1

Type RM Length L Ch R = 1 ,16855.1 ,271.2,297.1,322.9
XS GIS Cut Line= 5
      1837699.92      226164.778     1837041.961      225559.108
     1836967.886      225445.817     1836623.656      225463.246
     1835930.839      224827.074
#Sta/Elev= 30
       0 2090.93   219.8 2058.12   574.5 1960.04   604.5  1954.1   639.5 1954.79
   664.5 1944.32   694.4 1941.41   734.4 1925.88   779.4 1922.06     904 1899.24
     991 1864.35  1034.6  1858.6  1044.6 1862.94  1114.6 1861.72  1168.4 1829.52
  1174.5 1827.58  1183.4 1828.32  1239.4 1875.37  1324.4 1880.91  1374.3 1890.73
  1518.6 1956.82  1563.4 1971.19  1682.9 1988.66  1742.6 2004.33    1862 1996.72
  1951.6 2005.33  2001.4 2032.84  2150.7 2097.35  2275.1 2123.15  2314.9 2135.73
#Mann= 3 , 0 , 0
       0      .1       0  1168.4    .045       0  1183.4      .1       0
Bank Sta=1168.4,1183.4
XS Rating Curve= 0 ,0
Exp/Cntr=0.3,0.1

Type RM Length L Ch R = 1 ,16558   ,296.3,282.3,268.2
XS GIS Cut Line= 4
     1837922.608      225841.268     1837207.087      225614.301
     1836890.062      225008.783     1836146.143      224493.051
#Sta/Elev= 30
       0 2050.76   193.9 2000.34   263.5 1986.23   298.3 1986.04   382.8 2002.82
   452.4 2009.44   497.1 1998.67   551.8 1993.97   586.6 1978.69   705.9 1945.12
   750.7 1938.43   840.5 1946.51   905.3 1938.24   965.2 1899.38    1040 1864.35
  1089.9 1848.54  1158.2 1840.65  1164.7 1840.57  1173.2 1840.73  1249.6 1847.43
  1329.4 1876.57  1374.3 1909.27    1454 1978.06  1593.3 2070.02  1672.9 2107.76
  1802.2 2108.77  1861.9 2117.55  1911.6 2119.46  2249.8 2164.19  2339.4 2187.09
#Mann= 3 , 0 , 0
       0      .1       0  1158.2    .045       0  1173.2      .1       0
Bank Sta=1158.2,1173.2
XS Rating Curve= 0 ,0
Exp/Cntr=0.3,0.1

Type RM Length L Ch R = 1 ,16275.7 ,271,265.1,259.1
XS GIS Cut Line= 5
     1837998.437      225475.356     1837347.207       225114.23
     1837139.315      225007.175     1836915.729      224943.139
     1836524.535      224630.481
#Sta/Elev= 30
       0  1924.5      90 1911.25   184.9 1905.39   254.9 1904.64   344.8 1885.15
   419.8 1876.62   464.8 1867.98   539.8 1865.76   574.7 1858.83   619.7 1853.21
   674.7 1841.36   774.5 1845.41   814.3 1839.79   888.9 1821.83   927.6 1815.23
   933.7 1814.92   942.6 1815.83  1003.2 1835.36  1107.2 1893.15  1141.8 1918.69
  1206.1    1972  1225.9  1984.8  1275.5 2008.68  1399.5 2062.72  1419.3 2068.18
  1488.7 2080.95  1538.3 2086.68  1617.6 2085.72  1642.4  2088.7  1711.9 2091.95
#Mann= 3 , 0 , 0
       0      .1       0   927.6    .045       0   942.6      .1       0
Bank Sta=927.6,942.6
XS Rating Curve= 0 ,0
Exp/Cntr=0.3,0.1

Type RM Length L Ch R = 1 ,16010.6 ,37.3,39.5,41.8
XS GIS Cut Line= 4
     1838091.798      225281.841     1837395.318       224805.18
     1837021.361      224724.986     1836422.426      224400.394
#Sta/Elev= 30
       0 1931.72      30 1931.55    94.9 1935.73   149.8 1935.46   329.6 1933.25
   399.5 1928.38   544.3 1932.59   654.2 1942.27   694.2 1932.44   764.1 1902.69
   873.8 1843.25   898.6 1831.95   923.4 1823.64  1008.4 1806.32  1022.8 1805.44
  1023.4 1805.46  1052.6 1810.42  1127.1 1842.23  1166.8 1853.17  1276.2 1891.22
    1296  1900.7  1330.8 1923.22  1355.7 1934.51  1400.5 1947.16  1504.9 1971.31
  1629.2 2011.91  1683.9 2021.43  1753.5 2039.62  1828.1  2044.6  1907.7 2053.42
#Mann= 3 , 0 , 0
       0      .1       0  1008.4    .045       0  1023.4      .1       0
Bank Sta=1008.4,1023.4
XS Rating Curve= 0 ,0
Exp/Cntr=0.3,0.1

Type RM Length L Ch R = 1 ,15971.1 ,166.2,171.3,176.5
XS GIS Cut Line= 4
     1838134.744      225004.667     1837442.826      224797.392
     1837114.167      224693.031       1836535.1      224342.339
#Sta/Elev= 30
       0 2064.32    49.8 2064.41   114.6 2061.62   194.3 2053.98   224.2 2048.17
     274 2035.15   338.7 2008.01   398.5 1989.98   453.3 1982.88   513.1 1982.22
   552.9 1957.43   602.7 1931.49   717.3 1889.08   807.3 1839.31   847.2 1825.46
   938.6 1803.27   953.6 1800.73   957.2 1800.54   972.2  1803.9  1007.2 1821.34
  1037.1 1833.88  1131.8  1854.2  1201.5 1876.72  1246.3 1896.14    1321 1920.67
  1460.4 2003.16  1520.1 2027.58    1555  2038.5  1604.7 2048.74  1744.1 2067.27
#Mann= 3 , 0 , 0
       0      .1       0   938.6    .045       0   953.6      .1       0
Bank Sta=938.6,953.6
XS Rating Curve= 0 ,0
Exp/Cntr=0.3,0.1

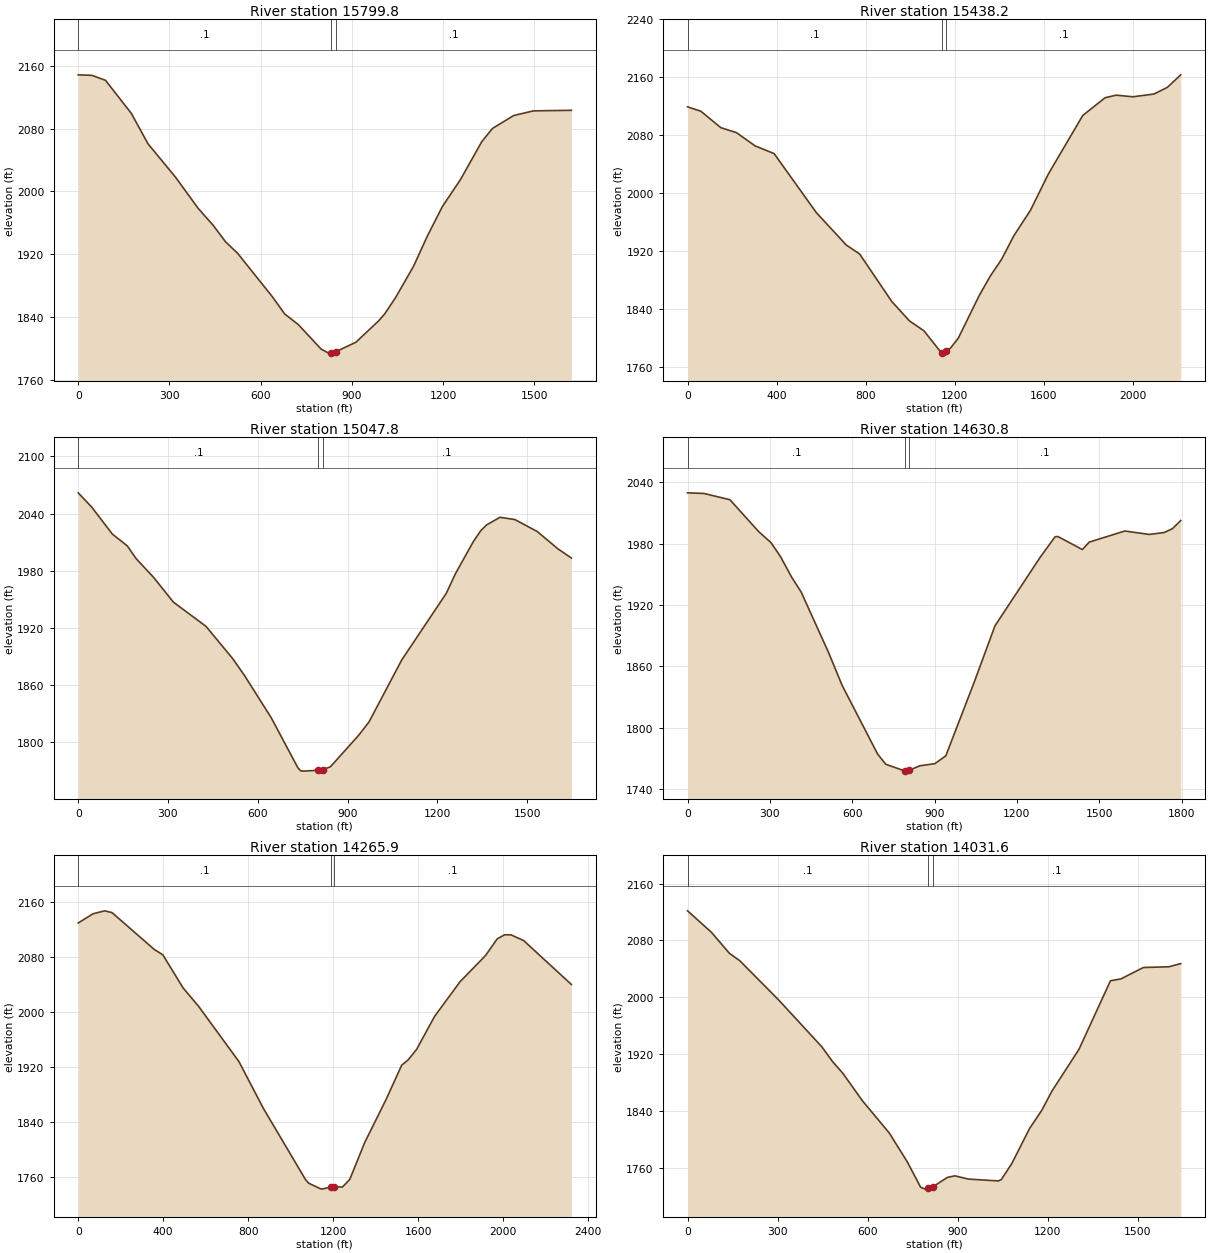
Type RM Length L Ch R = 1 ,15799.8 ,373.4,361.5,349.7
XS GIS Cut Line= 4
      1838080.92      224756.613     1837443.776      224663.172
     1837107.157      224469.511     1836553.678      224267.813
#Sta/Elev= 30
       0 2148.42    44.9 2147.76    89.8 2141.45   174.7 2099.28   229.6 2060.53
   319.5 2018.32   394.4  1978.4   444.3 1956.55   484.2 1935.91   524.2 1921.14
     639 1865.54   678.8 1843.93   723.6 1830.44   798.3 1799.33   823.2 1794.07
   831.4 1794.17   846.4 1795.71   912.8 1807.92   987.5 1835.09  1007.4 1843.91
  1042.3  1864.1  1102.2 1904.46  1147.1 1942.54    1197 1980.52    1257  2015.2
  1326.8 2063.36  1361.8  2080.1  1431.7  2096.6  1496.6 2102.54  1621.4 2103.24
#Mann= 3 , 0 , 0
       0      .1       0   831.4    .045       0   846.4      .1       0
Bank Sta=831.4,846.4
XS Rating Curve= 0 ,0
Exp/Cntr=0.3,0.1

Type RM Length L Ch R = 1 ,15438.2 ,373.7,390.4,407.2
XS GIS Cut Line= 4
      1838442.92      224625.852     1837611.424      224238.336
      1837229.21      224219.314     1836324.696      224082.034
#Sta/Elev= 30
       0 2119.26    59.8 2113.21   149.6 2090.52   219.4  2083.7   304.1  2065.3
   388.9 2054.75   578.3 1973.33     713 1928.61   772.8 1916.24   917.4 1850.65
   996.9 1823.87  1061.5 1810.34    1141  1779.5  1144.7 1779.97  1159.7 1781.93
  1180.8 1786.45  1215.6 1800.01    1310 1859.02    1360 1886.05    1410 1908.73
    1465 1941.22    1540 1976.58    1620  2026.4    1775 2107.38    1875 2131.82
    1925 2135.37    2000 2133.15  2094.9 2136.95  2154.9 2146.16  2214.9 2163.43
#Mann= 3 , 0 , 0
       0      .1       0  1144.7    .045       0  1159.7      .1       0
Bank Sta=1144.7,1159.7
XS Rating Curve= 0 ,0
Exp/Cntr=0.3,0.1

Type RM Length L Ch R = 1 ,15047.8 ,435.2,417,398.8
XS GIS Cut Line= 4
     1838283.807      224238.945     1837803.872      224110.915
     1837482.884      223809.741     1836802.474      223602.246
#Sta/Elev= 30
       0 2061.87    44.7 2047.08   114.2 2018.57   163.9 2006.26   193.7 1992.77
   253.3 1972.69   317.9 1947.24   427.2 1921.74   516.5 1887.86   556.1 1870.04
   645.1 1825.89   734.1  1773.4     744 1770.13   753.9 1769.87   802.8 1770.84
   817.8 1771.47   842.9 1774.44   936.9 1807.34   971.7 1821.42  1081.1 1886.46
  1230.4  1956.6  1260.2 1976.73  1319.9  2010.4  1344.8 2021.98  1364.7 2028.18
  1409.4  2036.2  1459.2 2033.83  1533.8 2021.33  1603.4 2003.03  1648.2 1993.43
#Mann= 3 , 0 , 0
       0      .1       0   802.8    .045       0   817.8      .1       0
Bank Sta=802.8,817.8
XS Rating Curve= 0 ,0
Exp/Cntr=0.3,0.1

Type RM Length L Ch R = 1 ,14630.8 ,370.1,364.9,359.5
XS GIS Cut Line= 4
      1838528.02      223704.917     1838054.802      223533.088
     1837682.449      223549.783     1836778.335       223376.16
#Sta/Elev= 30
       0 2029.66    59.8 2029.04   154.5  2022.9   259.2 1991.74   304.1 1980.96
     339 1967.17   378.8 1947.41   413.7 1932.82   513.4  1873.8   563.1 1841.49
   692.3 1774.44   722.1 1764.38   792.2 1757.76   796.7 1757.66   807.2 1758.47
   846.4 1762.88   901.1 1764.95   940.9 1772.62  1045.4 1845.36    1120 1899.67
  1284.2  1966.5    1339 1986.73  1348.9 1986.98  1438.5 1974.22  1463.4 1981.49
  1592.8 1992.34  1682.4 1988.98  1737.1 1990.89    1767 1994.73  1796.8  2002.6
#Mann= 3 , 0 , 0
       0      .1       0   792.2    .045       0   807.2      .1       0
Bank Sta=792.2,807.2
XS Rating Curve= 0 ,0
Exp/Cntr=0.3,0.1

Type RM Length L Ch R = 1 ,14265.9 ,208.4,234.3,259.6
XS GIS Cut Line= 4
     1838933.887      223534.216     1838311.171       223232.39
     1837720.711       223203.36     1836684.942       223132.94
#Sta/Elev= 30
       0  2129.9    69.7 2143.28   124.5 2147.58   159.3 2144.96   358.4 2091.32
   398.3 2083.69   492.9 2035.84   567.6 2008.34   756.6 1928.34   870.8 1860.76
  1069.6 1756.92  1084.5 1751.61  1144.1 1742.94  1188.4 1745.64  1203.4 1746.49
  1243.4  1745.9  1278.2 1757.12  1348.1 1810.49  1447.9 1872.54  1522.8 1923.27
  1552.7 1930.73  1592.6 1946.07  1677.5 1994.19  1797.3 2044.56  1917.1 2082.55
    1972 2106.78  2006.9 2112.73  2036.8 2112.68  2096.7  2104.3  2321.3  2040.5
#Mann= 3 , 0 , 0
       0      .1       0  1188.4    .045       0  1203.4      .1       0
Bank Sta=1188.4,1203.4
XS Rating Curve= 0 ,0
Exp/Cntr=0.3,0.1

Type RM Length L Ch R = 1 ,14031.6 ,226.9,208.9,191
XS GIS Cut Line= 4
     1838699.881      223298.882     1838008.544      223128.602
     1837841.669      222937.888     1837163.955       222920.86
#Sta/Elev= 30
       0 2121.67    79.7 2091.39   139.4 2061.84   174.3 2051.28   303.7 1996.06
   448.1 1929.78     483 1909.36   517.8 1892.62   582.5 1854.16   672.2 1808.64
   731.9 1768.21   776.6 1732.26   791.5 1729.59   802.4 1730.54   817.4 1732.85
     866 1746.16   890.9  1748.3   935.6 1743.75  1035.2 1741.14  1045.2 1742.92
  1080.1 1765.42  1139.9 1815.24  1179.8  1840.3  1214.6 1868.01  1304.4 1926.68
  1409.1 2023.14    1444 2025.76  1518.7 2041.81  1603.5 2042.85  1643.3 2047.27
#Mann= 3 , 0 , 0
       0      .1       0   802.4    .045       0   817.4      .1       0
Bank Sta=802.4,817.4
XS Rating Curve= 0 ,0
Exp/Cntr=0.3,0.1