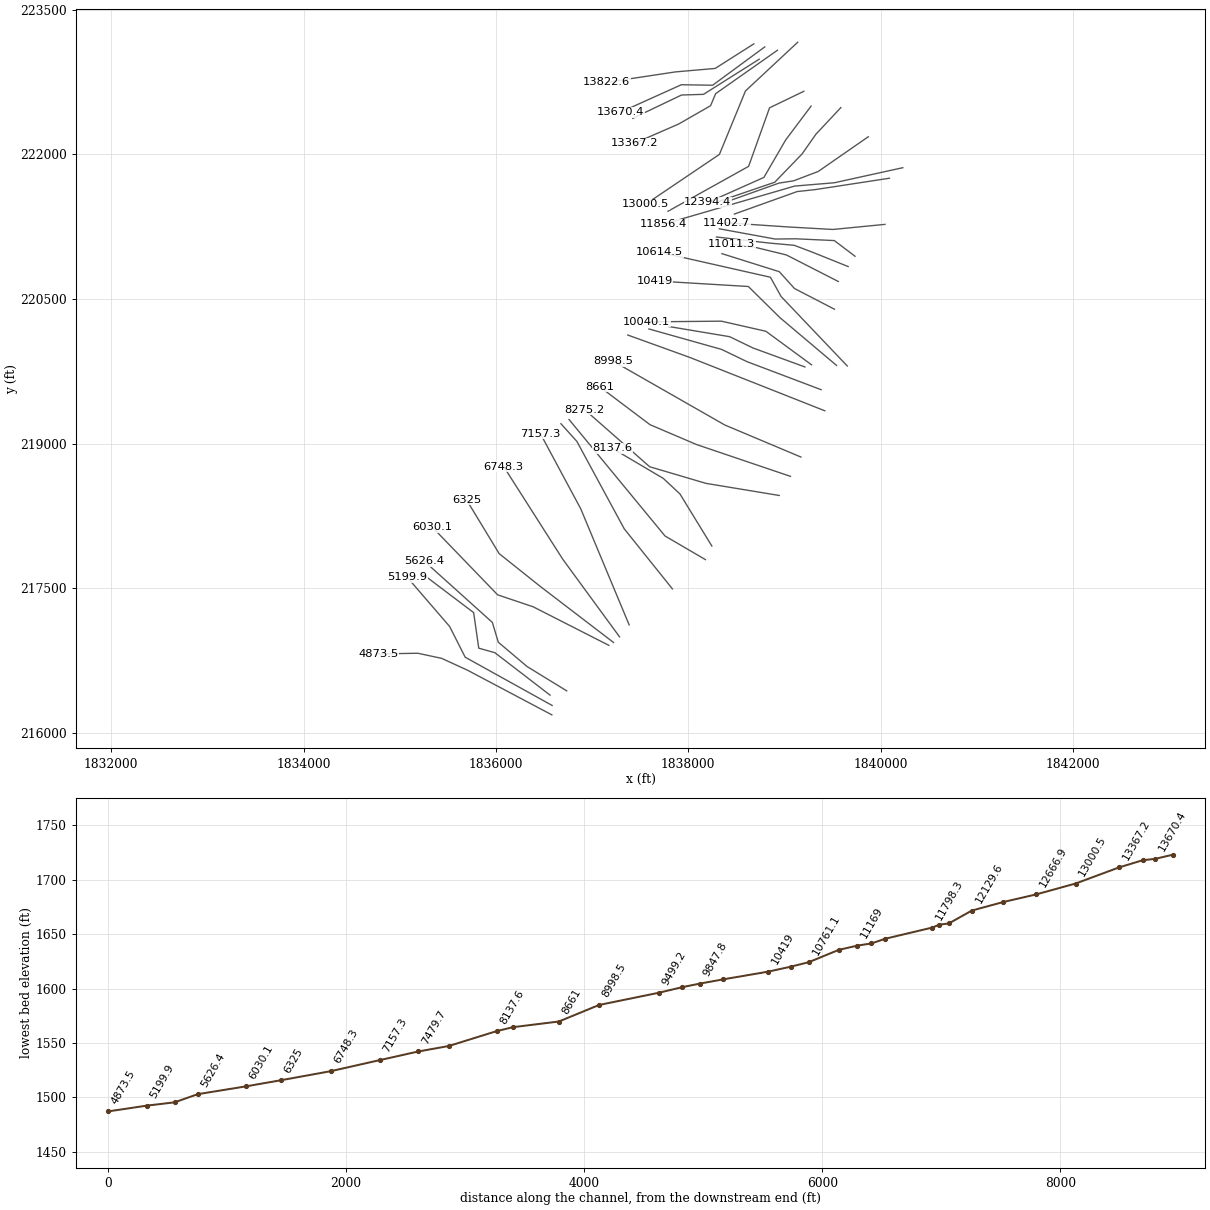
HEC-RAS study CabinCr.prj: CabinCr

--- CabinCr.g01 (geometry) --- (continued)

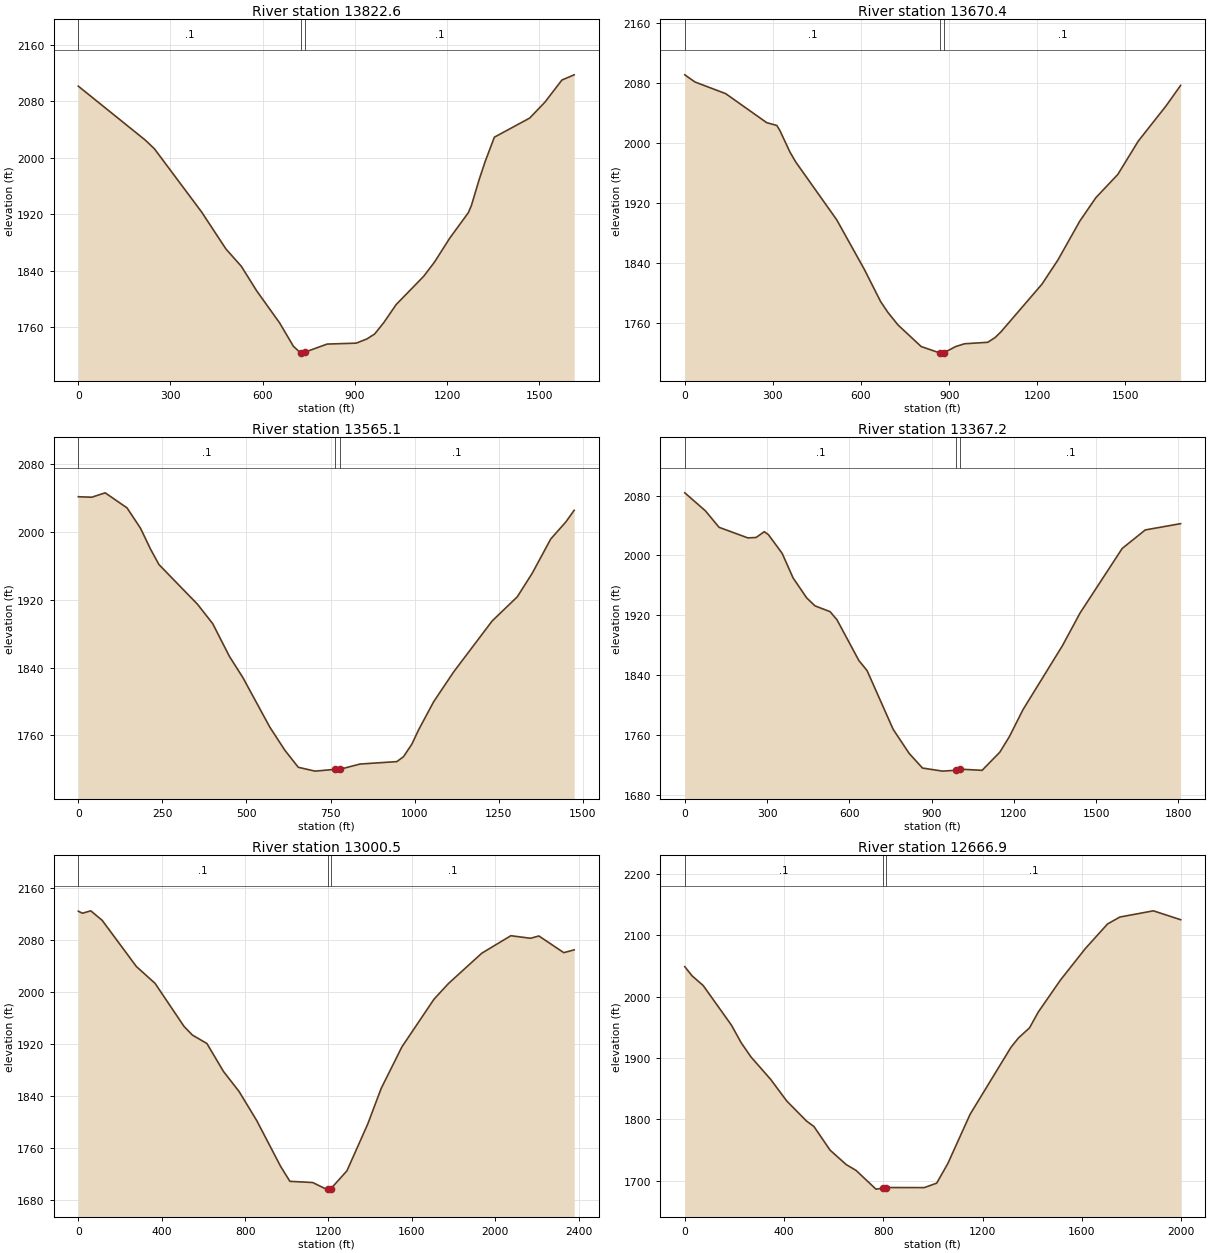
Type RM Length L Ch R = 1 ,13822.6 ,154.6,152.2,149.8
XS GIS Cut Line= 4
     1838681.392      223144.559      1838279.81      222889.965
     1837867.212      222853.967        1837151.       222746.11
#Sta/Elev= 30
       0 2101.62   217.9 2025.22   247.6 2012.93   401.2 1923.37   480.5 1870.86
   530.4 1846.41   580.3  1811.7   655.1 1766.14     700 1732.98   723.6 1723.46
     725 1723.24   738.6 1724.78   809.8 1736.08   904.6 1737.39   939.6 1743.41
   964.6  1750.4   994.6 1766.71  1034.5 1792.06  1124.4  1832.3  1159.4 1852.34
  1209.3 1886.46  1269.3 1922.18  1279.3 1932.32  1304.2 1968.58  1324.2 1994.77
  1354.2 2029.32  1469.1 2056.42    1519  2079.1    1574 2110.33  1613.9 2117.72
#Mann= 3 , 0 , 0
       0      .1       0   723.6    .045       0   738.6      .1       0
Bank Sta=723.6,738.6
XS Rating Curve= 0 ,0
Exp/Cntr=0.3,0.1

Type RM Length L Ch R = 1 ,13670.4 ,104.3,105.3,106.3
XS GIS Cut Line= 4
     1838794.712      223112.776     1838253.196      222715.665
     1837928.069      222720.844     1837297.749      222437.318
#Sta/Elev= 30
       0 2091.32    34.8 2081.72   139.3 2066.15   278.6 2027.43   313.4  2023.6
   323.3  2017.2   358.1 1987.98     378 1974.63   517.3 1897.44   611.8 1830.78
   666.5 1788.31   691.2 1773.84   725.7 1756.99   804.5 1728.16   868.1  1719.5
   873.5  1719.3   883.1 1720.05   922.8 1728.21   952.4 1731.81  1031.5  1733.8
  1056.4 1740.14  1076.2 1747.75  1215.5 1811.35  1270.2 1843.85  1344.8 1895.92
  1399.4 1927.15    1474 1958.17  1543.6 2002.68  1638.1 2049.76  1687.8 2077.18
#Mann= 3 , 0 , 0
       0      .1       0   868.1    .045       0   883.1      .1       0
Bank Sta=868.1,883.1
XS Rating Curve= 0 ,0
Exp/Cntr=0.3,0.1

Type RM Length L Ch R = 1 ,13565.1 ,185.1,197.9,209.9
XS GIS Cut Line= 4
     1838737.342      222985.566      1838158.39      222621.167
     1837930.215      222614.356      1837422.78      222372.558
#Sta/Elev= 30
       0  2041.1      40 2040.53    79.9  2045.7   144.8 2027.99   184.8 2004.11
   214.7 1979.41   239.7 1961.28   354.5 1914.47   399.5 1891.76   449.4  1853.1
   489.4 1828.15   569.2 1770.02   614.2 1742.61   654.1 1722.57   703.9 1718.03
   761.8 1720.07   776.8 1720.09   837.9 1726.38   947.2 1729.24   967.1 1735.06
     992 1749.88  1011.8 1766.59  1056.6 1799.66  1116.3 1834.92  1230.7 1894.87
  1305.3 1923.23  1350.1  1951.2  1404.8 1991.31  1449.6 2011.33  1474.5 2025.15
#Mann= 3 , 0 , 0
       0      .1       0   761.8    .045       0   776.8      .1       0
Bank Sta=761.8,776.8
XS Rating Curve= 0 ,0
Exp/Cntr=0.3,0.1

Type RM Length L Ch R = 1 ,13367.2 ,352.8,366.8,381.5
XS GIS Cut Line= 5
     1838926.992       223078.39     1838284.309      222628.075
     1838231.846      222503.473     1837899.574      222313.292
     1837436.144       222112.18
#Sta/Elev= 30
       0 2083.69      75 2059.68     125 2037.55   229.9 2023.42   259.9 2023.96
   289.9 2031.72   304.9 2027.74   354.9 2002.82   394.9 1969.87   444.9 1942.97
   474.8 1932.51   529.8 1924.75   554.8    1914   634.8 1859.37   664.8 1845.87
   759.8 1767.37   818.5 1734.99   866.8 1715.59   939.8 1711.47   988.6 1712.63
  1003.6  1714.1    1084 1712.52  1148.7 1736.81  1183.5 1757.54  1233.2  1793.7
  1377.1 1879.31  1441.5 1923.07    1595 2009.32  1679.2 2034.08    1808 2042.46
#Mann= 3 , 0 , 0
       0      .1       0   988.6    .045       0  1003.6      .1       0
Bank Sta=988.6,1003.6
XS Rating Curve= 0 ,0
Exp/Cntr=0.3,0.1

Type RM Length L Ch R = 1 ,13000.5 ,326.3,333.6,349.1
XS GIS Cut Line= 4
     1839137.394      223161.191     1838594.721      222656.493
     1838323.657      221998.509     1837555.857      221481.532
#Sta/Elev= 30
       0  2124.5    19.9 2121.41    59.7 2125.11   114.4 2110.49   278.5 2039.33
   368.1 2013.44   507.3 1947.01   547.1 1933.85   616.8  1920.8   696.3 1877.76
     771 1846.96   855.6 1802.24     970 1731.82  1014.8 1708.59  1124.3 1706.74
    1189 1696.58  1195.6 1696.67  1210.6 1696.96  1288.5 1724.82    1388 1796.61
  1452.7 1851.64  1552.2 1915.65  1706.5 1989.22  1776.2  2013.4  1935.4 2059.88
  2074.8  2086.8  2169.3 2082.84  2209.2  2086.4  2328.6 2060.71  2378.4 2064.98
#Mann= 3 , 0 , 0
       0      .1       0  1195.6    .045       0  1210.6      .1       0
Bank Sta=1195.6,1210.6
XS Rating Curve= 0 ,0
Exp/Cntr=0.3,0.1

Type RM Length L Ch R = 1 ,12666.9 ,288.1,272.4,248.5
XS GIS Cut Line= 4
     1839201.419      222652.779     1838844.844      222481.423
     1838627.201      221874.605     1837789.419      221409.295
#Sta/Elev= 30
       0 2048.92    29.7 2033.91    74.2 2018.21   187.9 1953.76   227.5  1924.9
     267 1901.79   346.2  1865.3   410.6 1830.27   490.6 1797.46   520.6 1788.54
   585.5 1750.09   650.5 1726.54   690.5 1716.96   770.4 1686.51     797 1687.89
     812 1689.12   965.3 1688.99  1015.3 1696.25  1060.2 1728.18  1150.1  1808.5
  1314.8 1917.61  1344.8 1932.77  1389.7 1949.36  1424.6 1974.88  1514.4 2027.27
  1614.3 2078.36  1704.1 2118.56    1754 2129.86  1888.8 2139.94  1998.6 2125.48
#Mann= 3 , 0 , 0
       0      .1       0     797    .045       0     812      .1       0
Bank Sta=797,812
XS Rating Curve= 0 ,0
Exp/Cntr=0.3,0.1

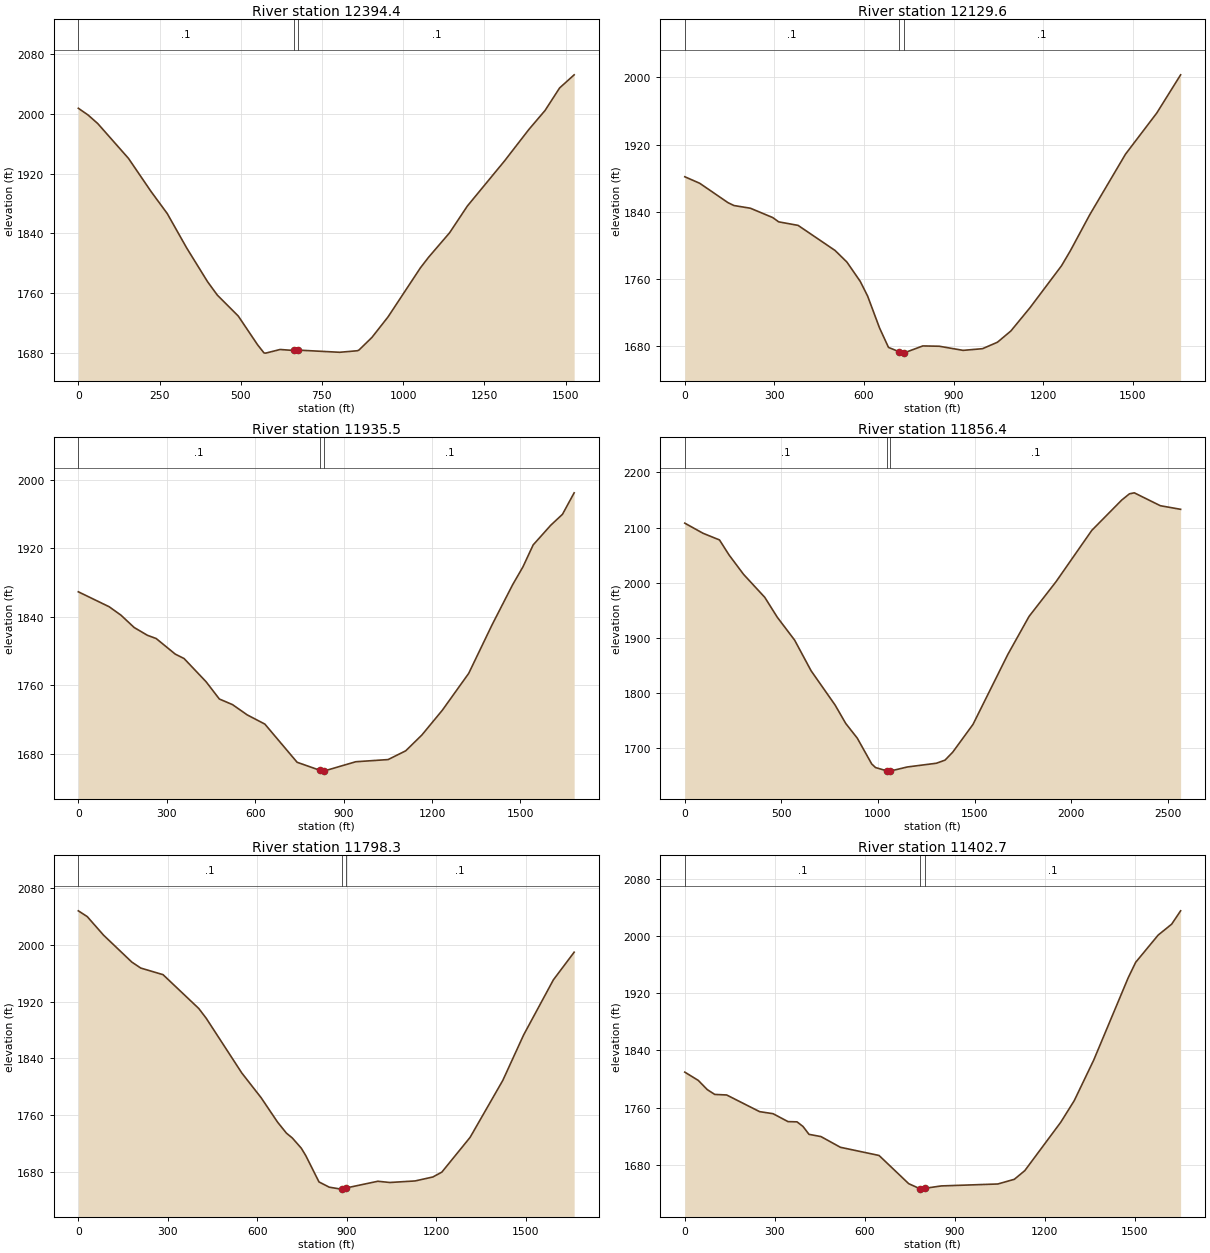
Type RM Length L Ch R = 1 ,12394.4 ,265.4,264.8,264.2
XS GIS Cut Line= 4
     1839276.761      222499.162     1839013.228      222149.399
      1838786.16      221759.877     1838203.645      221500.594
#Sta/Elev= 30
       0 2007.48    29.9  1998.5    59.7 1987.05   154.3 1940.43   223.9 1896.01
   273.7 1866.52   333.4 1820.54   398.1 1775.06     428 1757.26   492.4 1729.25
   551.9 1690.73   571.7 1679.86   576.7 1679.61   621.2 1684.48   662.7 1683.16
   677.7 1683.63   804.6 1680.74   859.1 1682.81     864 1683.75   903.8 1700.62
   953.6 1728.21  1053.2 1793.86  1078.1 1807.91  1142.8 1840.69  1197.6 1876.54
  1312.2 1937.05  1386.9 1979.04  1436.8 2004.53  1481.6 2034.68  1526.4 2052.26
#Mann= 3 , 0 , 0
       0      .1       0   662.7    .045       0   677.7      .1       0
Bank Sta=662.7,677.7
XS Rating Curve= 0 ,0
Exp/Cntr=0.3,0.1

Type RM Length L Ch R = 1 ,12129.6 ,204.2,194.1,184.1
XS GIS Cut Line= 5
     1839586.166      222483.584     1839326.533      222207.201
     1839184.154      222004.521     1838899.136      221710.096
     1838309.393      221508.965
#Sta/Elev= 30
       0 1881.64    49.9 1873.88   144.7  1850.8   164.6  1847.4   219.5  1844.2
   294.4 1833.07   314.3 1827.98   379.2 1823.78     503 1793.93   542.7 1780.12
   587.3 1757.14     612 1739.68   651.9 1701.73   681.9 1678.56   718.2 1673.31
   731.8 1671.76   733.2 1671.91   796.8 1680.33   851.8 1679.96   931.7 1675.04
   996.7 1677.05  1046.6 1684.73  1091.5 1698.09  1156.3 1726.14    1261 1775.68
  1290.9 1793.68  1355.7 1836.51  1475.3 1908.51    1580 1957.49  1659.8 2002.93
#Mann= 3 , 0 , 0
       0      .1       0   718.2    .045       0   733.2      .1       0
Bank Sta=718.2,733.2
XS Rating Curve= 0 ,0
Exp/Cntr=0.3,0.1

Type RM Length L Ch R = 1 ,11935.5 ,85.5,79.2,72.8
XS GIS Cut Line= 5
     1839871.386      222181.472     1839350.846      221821.557
     1839095.069      221724.593     1838942.301      221700.792
     1838357.001      221492.576
#Sta/Elev= 30
       0 1869.31   104.6 1851.86   144.5 1842.06   189.4 1827.62   234.2 1818.54
   264.1 1814.73   328.9 1796.52   358.8 1791.35   433.5 1764.24   478.4 1744.11
   523.2 1737.52     573 1725.54   632.8  1714.8   742.3 1670.19     820 1660.79
   831.8 1659.86     835 1660.12   941.3 1670.82    1051 1673.36  1110.7 1683.57
  1165.4 1701.98    1235 1731.01  1324.4 1774.01  1403.9 1830.88  1473.5 1877.59
  1508.3 1898.33  1543.1 1924.06  1602.7 1947.02  1642.5  1959.8  1682.2 1984.91
#Mann= 3 , 0 , 0
       0      .1       0     820    .045       0     835      .1       0
Bank Sta=820,835
XS Rating Curve= 0 ,0
Exp/Cntr=0.3,0.1

Type RM Length L Ch R = 1 ,11856.4 ,57.5,58.1,58.7
XS GIS Cut Line= 4
     1840230.686      221860.757     1839519.168       221704.61
     1839106.916      221670.342     1837738.529      221273.645
#Sta/Elev= 30
       0 2107.91    94.8 2089.52   179.6 2077.52   229.5  2050.1   304.4 2015.11
   414.1 1973.51     479 1937.42   568.8 1895.92   653.6 1840.68   778.3 1778.38
   833.1 1745.16   892.9 1718.52   967.7 1671.72   987.6 1665.25  1046.9 1659.11
  1061.9 1658.78  1152.1 1666.32  1302.1 1673.03  1347.1 1678.68  1387.1 1693.14
  1492.1  1743.5    1672 1869.93    1782  1938.9    1922 2001.97  2106.9 2094.81
  2261.9 2149.75  2301.9 2161.04  2326.9 2162.84  2461.9 2139.49  2566.8 2132.97
#Mann= 3 , 0 , 0
       0      .1       0  1046.9    .045       0  1061.9      .1       0
Bank Sta=1046.9,1061.9
XS Rating Curve= 0 ,0
Exp/Cntr=0.3,0.1

Type RM Length L Ch R = 1 ,11798.3 ,399.7,395.6,391.4
XS GIS Cut Line= 4
     1840091.588      221751.616     1839322.907      221633.998
     1839131.838      221613.229     1838479.094      221379.976
#Sta/Elev= 30
       0 2047.65    29.9 2039.52    84.7 2013.38   179.4 1975.54   209.4 1967.13
   284.1 1957.84   403.8 1910.32   428.7 1896.64   548.3 1819.51   613.1 1784.73
     668 1750.51   697.9 1734.91   717.8 1728.04   747.7 1713.75   762.7  1703.4
   807.2 1666.24   841.7 1658.83   881.1 1656.12   883.4 1656.29   898.4 1657.77
  1004.7 1667.19  1044.6 1665.46  1129.4 1667.62  1189.2 1673.21  1219.2 1680.02
  1313.9 1728.89  1423.6 1809.02  1493.4 1872.92  1593.2 1950.48    1663 1989.44
#Mann= 3 , 0 , 0
       0      .1       0   883.4    .045       0   898.4      .1       0
Bank Sta=883.4,898.4
XS Rating Curve= 0 ,0
Exp/Cntr=0.3,0.1

Type RM Length L Ch R = 1 ,11402.7 ,116.9,117.2,117.4
XS GIS Cut Line= 4
       1840044.8       221273.02     1839503.372      221220.253
     1839034.062      221246.652     1838395.797      221289.325
#Sta/Elev= 30
       0 1809.59    44.9 1798.05    74.9 1785.17    99.8 1778.42   139.7 1777.62
   249.5  1754.3   294.4 1751.42   344.4 1740.32   374.3 1740.02   394.3 1733.52
   414.2 1722.55   454.2 1719.38     519  1704.4   647.9 1692.95   746.9 1653.45
   784.7  1646.3   791.4 1645.84   799.7 1646.93   855.7 1650.32    1044 1653.03
    1099 1659.58    1134 1671.72  1253.9 1739.46  1298.9 1769.68  1363.9 1826.52
  1478.8 1941.64  1503.8 1963.35  1578.8 2001.46  1623.8 2016.73  1653.7  2035.4
#Mann= 3 , 0 , 0
       0      .1       0   784.7    .045       0   799.7      .1       0
Bank Sta=784.7,799.7
XS Rating Curve= 0 ,0
Exp/Cntr=0.3,0.1

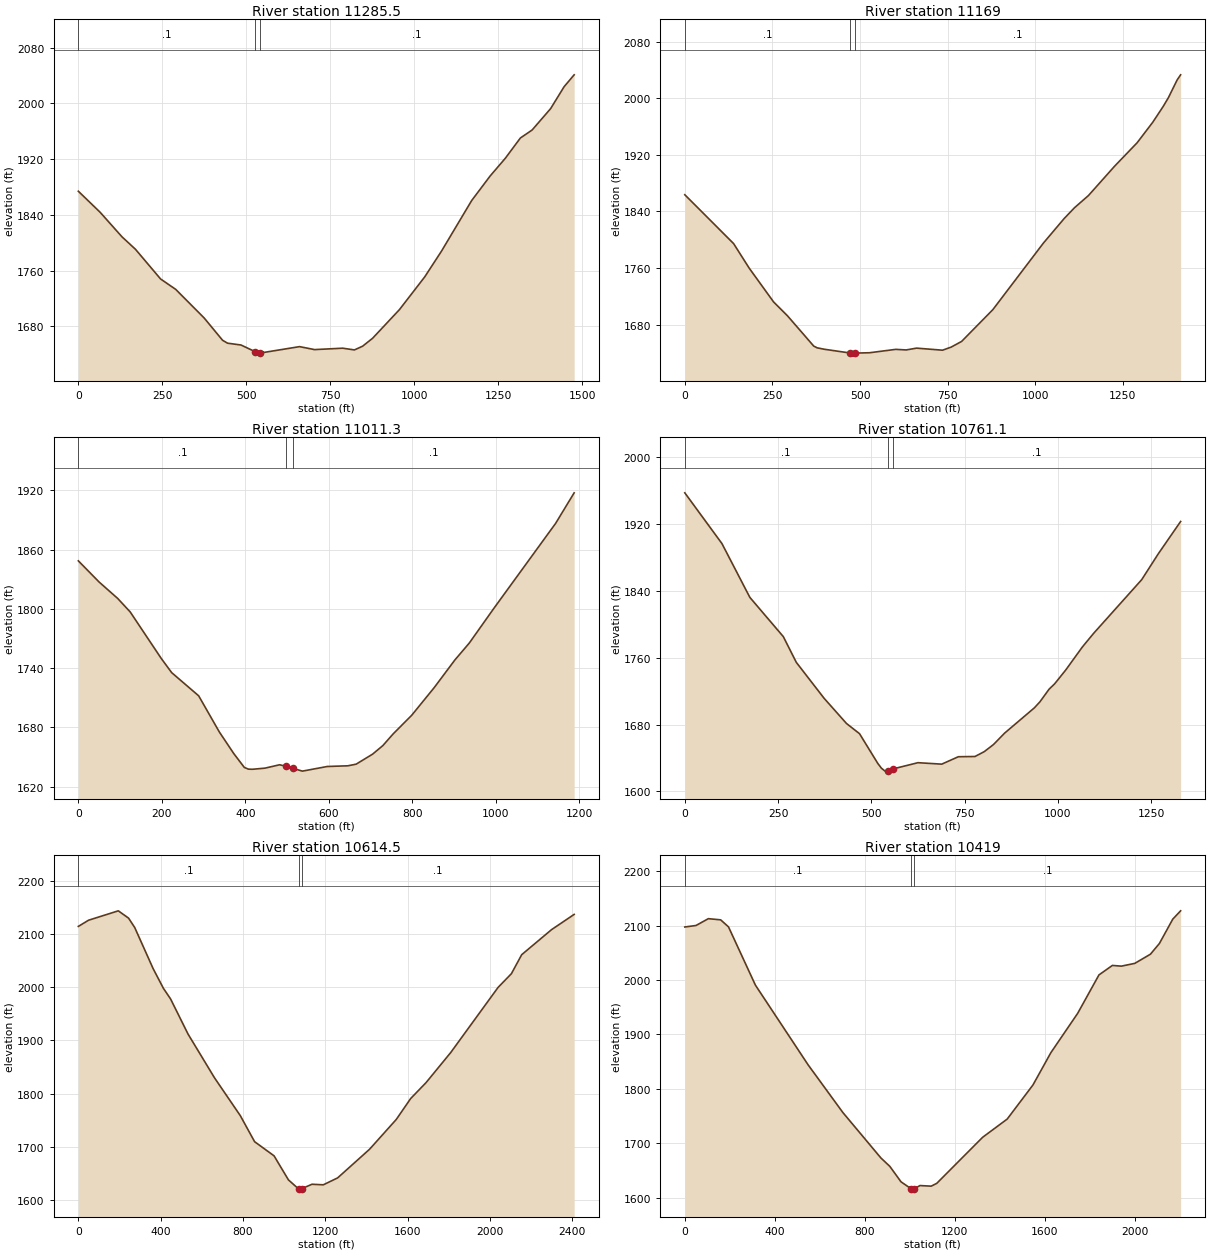
Type RM Length L Ch R = 1 ,11285.5 ,124,116.5,109.1
XS GIS Cut Line= 5
      1839733.51      220942.544     1839518.223      221105.127
     1839115.215      221123.572     1838902.886      221120.942
     1838322.829      221227.155
#Sta/Elev= 30
       0 1873.94      65 1843.66   129.9 1808.47   169.9 1790.64   244.8 1747.92
   289.7 1733.04   374.4 1691.95   429.2 1659.93   444.1 1655.75     484 1653.13
   526.1  1643.6   538.7 1641.48   541.1 1641.62   658.3 1650.81   702.8 1646.54
   786.8 1648.56   821.4 1646.08     846 1651.45   875.7 1662.87   955.5 1703.96
  1030.5 1750.83  1080.5 1787.84  1170.4 1860.58  1225.4 1895.85  1270.4  1921.2
  1315.3 1950.34  1350.3 1961.87  1405.3 1992.52  1445.3 2023.93  1475.3 2041.05
#Mann= 3 , 0 , 0
       0      .1       0   526.1    .045       0   541.1      .1       0
Bank Sta=526.1,541.1
XS Rating Curve= 0 ,0
Exp/Cntr=0.3,0.1

Type RM Length L Ch R = 1 ,11169   ,160.4,157.8,155.1
XS GIS Cut Line= 5
      1839661.85      220835.787     1839297.457      220982.022
     1839101.525      221055.995     1838840.472       221079.46
     1838293.236      221142.332
#Sta/Elev= 30
       0 1863.55   139.2 1794.52   183.9 1759.66   253.5 1711.88   293.2 1692.24
   367.8 1649.58   377.7 1647.04   397.6 1645.07   471.9  1639.7   482.4 1639.54
   486.9 1639.58   527.3 1640.08   602.1 1644.87   631.7 1644.05   661.4  1646.6
   735.6 1643.68   760.3 1648.08     790 1656.09   879.1 1701.02    1023 1794.94
  1082.5  1829.8  1112.3 1845.25    1152 1862.44  1226.4 1903.82    1291 1937.15
  1335.6 1966.16  1365.4 1988.55  1380.3 2001.01  1405.1 2025.95    1415 2033.16
#Mann= 3 , 0 , 0
       0      .1       0   471.9    .045       0   486.9      .1       0
Bank Sta=471.9,486.9
XS Rating Curve= 0 ,0
Exp/Cntr=0.3,0.1

Type RM Length L Ch R = 1 ,11011.3 ,258.4,250.1,241.5
XS GIS Cut Line= 4
     1839559.723      220680.908     1839019.396      220956.267
     1838693.813      221035.463     1838449.375      221066.394
#Sta/Elev= 30
       0 1848.56    49.7 1827.14    94.4 1810.44   124.3 1796.79   198.8 1749.62
   223.7 1735.31   288.3 1711.86     338 1675.11   372.8 1653.13   397.7 1639.33
   407.6 1637.58   417.6 1637.46   447.4 1638.62   482.2 1642.01   498.5 1640.42
   513.5 1638.48   536.8 1635.58   596.5 1640.28   645.9 1640.97   665.6 1642.63
     705 1652.77   729.6 1661.46   754.3  1673.3   798.6  1692.1   852.8 1720.27
   902.1 1748.14   936.6 1765.25   995.7 1800.53  1143.6 1886.56  1187.9 1917.44
#Mann= 3 , 0 , 0
       0      .1       0   498.5    .045       0   513.5      .1       0
Bank Sta=498.5,513.5
XS Rating Curve= 0 ,0
Exp/Cntr=0.3,0.1

Type RM Length L Ch R = 1 ,10761.1 ,151.8,146.6,141.8
XS GIS Cut Line= 4
     1839520.068      220393.177     1839104.148      220608.053
     1838946.449      220782.352     1838349.776      220969.562
#Sta/Elev= 30
       0 1957.27    99.6 1896.51   174.3  1832.2     264 1785.22   298.8 1754.44
   373.5 1711.33   433.3 1681.29   468.2 1669.11   517.1 1633.57   526.9 1627.79
   536.7 1624.31   543.2 1624.82   558.2 1627.01   624.8  1634.4   688.5 1632.66
     733 1641.53   777.6 1641.82   802.5 1647.63   827.3 1656.18     857 1669.78
   936.5 1699.94   951.4 1707.12   976.2 1722.37   991.1 1728.78  1020.8 1745.33
  1065.5 1772.94  1095.3 1789.06  1224.3 1853.37    1269 1884.48  1328.6 1922.98
#Mann= 3 , 0 , 0
       0      .1       0   543.2    .045       0   558.2      .1       0
Bank Sta=543.2,558.2
XS Rating Curve= 0 ,0
Exp/Cntr=0.3,0.1

Type RM Length L Ch R = 1 ,10614.5 ,189,195.5,202
XS GIS Cut Line= 4
      1839653.06      219804.723     1838965.322      220524.917
     1838853.598      220724.952      1837698.66      220985.531
#Sta/Elev= 30
       0 2114.14    49.8 2125.79   194.2 2143.43     244  2129.7   273.8 2112.21
   363.5  2034.7   413.3 1997.78   448.1 1977.84   532.8 1911.91   662.2 1829.18
   786.7 1758.56   856.4 1709.46     951 1682.84  1020.7  1637.7    1071 1620.33
  1075.5 1620.28    1086 1621.22  1135.3 1629.45  1190.1 1628.37  1259.9 1641.42
  1414.8 1695.21  1544.7 1751.25  1614.6 1790.56  1689.5 1820.53  1809.4 1877.13
  2039.2 1999.43  2104.2 2025.36  2154.1 2060.99    2299 2108.03  2408.9 2136.72
#Mann= 3 , 0 , 0
       0      .1       0    1071    .045       0    1086      .1       0
Bank Sta=1071,1086
XS Rating Curve= 0 ,0
Exp/Cntr=0.3,0.1

Type RM Length L Ch R = 1 ,10419   ,365.9,378.9,391.8
XS GIS Cut Line= 4
     1839541.284      219810.679     1838953.959      220304.983
     1838624.434       220628.97      1837651.09      220687.121
#Sta/Elev= 30
       0 2097.61    49.8 2100.36   104.7  2112.9   159.5 2110.74   194.4 2097.78
     314 1990.69   548.3 1844.16   702.8 1756.48     872 1672.89   911.8 1657.38
   961.4 1629.04  1005.1 1616.61  1011.1 1615.56  1020.1 1616.26  1045.9 1622.12
  1095.6 1621.02  1120.4 1626.18  1324.3 1710.84  1433.7 1744.41  1548.2  1807.1
  1627.8 1866.46  1747.2 1938.93  1841.7 2009.49  1901.4 2026.92  1941.2  2025.6
  2000.9 2030.69  2070.5 2047.54  2110.3 2067.18    2170 2112.08  2204.8 2127.33
#Mann= 3 , 0 , 0
       0      .1       0  1005.1    .045       0  1020.1      .1       0
Bank Sta=1005.1,1020.1
XS Rating Curve= 0 ,0
Exp/Cntr=0.3,0.1

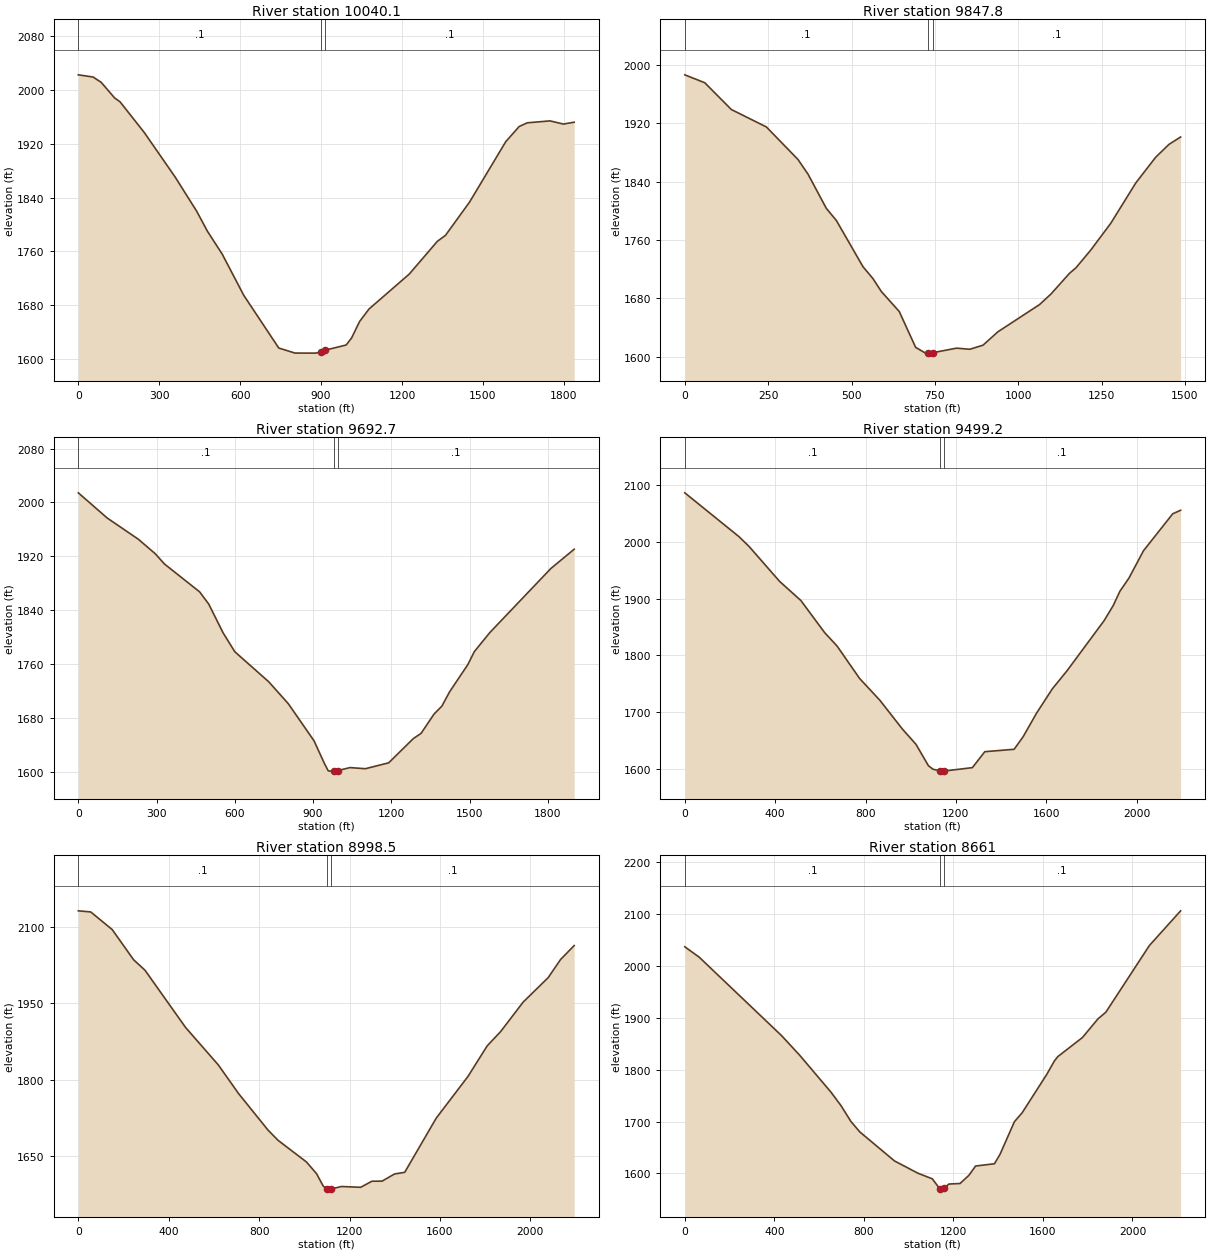
Type RM Length L Ch R = 1 ,10040.1 ,197.3,192.3,186.1
XS GIS Cut Line= 4
     1839281.378      219817.067      1838806.79      220164.678
     1838343.984      220269.532     1837568.515       220262.19
#Sta/Elev= 30
       0 2022.69    54.8  2019.4    84.8 2011.49   134.6 1988.28   154.6 1982.56
   244.3 1936.94     359 1870.55   438.7 1819.77   478.6 1789.91   533.4 1755.89
   613.2 1694.63   743.1 1616.07   803.1 1608.55     878 1608.45   899.6 1609.93
   914.6  1612.8   992.9 1620.51  1012.9 1630.88  1042.8  1655.5  1077.7 1674.11
  1226.9 1726.09  1331.2 1774.92  1361.1 1783.69  1450.6 1833.34  1584.8 1923.24
  1634.5 1945.76  1664.3 1951.26  1748.8 1954.14  1798.5  1949.4  1838.3 1952.14
#Mann= 3 , 0 , 0
       0      .1       0   899.6    .045       0   914.6      .1       0
Bank Sta=899.6,914.6
XS Rating Curve= 0 ,0
Exp/Cntr=0.3,0.1

Type RM Length L Ch R = 1 ,9847.8  ,155.1,155.1,155.1
XS GIS Cut Line= 4
     1839212.986      219794.724      1838673.28      219991.248
     1838429.826      220108.576     1837796.257       220214.17
#Sta/Elev= 30
       0  1986.3    59.9 1975.44   139.8 1938.66   244.7 1914.82   339.6 1870.12
   369.6 1850.02   424.5 1803.11   454.5 1786.58   534.4 1723.13   564.4 1706.76
   589.1 1689.32   643.2 1661.65   692.3 1612.53   721.8 1604.64   728.1 1604.76
   743.1 1605.16   815.1 1611.48   854.6 1609.91   894.4 1615.55   939.2 1633.97
  1063.7 1671.17  1098.6 1685.95  1153.3 1713.92  1173.2 1721.73  1218.1 1746.38
  1277.8 1782.95  1352.5  1838.1  1412.2 1873.34  1452.1 1890.98  1486.9 1901.05
#Mann= 3 , 0 , 0
       0      .1       0   728.1    .045       0   743.1      .1       0
Bank Sta=728.1,743.1
XS Rating Curve= 0 ,0
Exp/Cntr=0.3,0.1

Type RM Length L Ch R = 1 ,9692.7  ,191.8,193.5,195.2
XS GIS Cut Line= 4
     1839380.613      219559.211     1838608.798      219850.383
     1838347.117      219976.378     1837590.675      220188.744
#Sta/Elev= 30
       0 2014.36     110 1977.18     230 1945.49     295 1923.91     330 1908.77
     465 1867.38     500 1849.19   554.9 1806.57   599.9 1778.46   729.9 1733.89
   804.9 1701.38   903.7 1646.22     943 1613.01   957.8 1601.86   962.8 1601.19
   979.9  1602.1   994.9 1601.98  1041.5 1606.44  1100.6 1604.78  1189.9 1613.52
  1284.4 1649.51  1314.2 1657.29    1364 1685.99  1393.8 1697.67  1423.6 1719.09
  1493.3 1759.29  1518.1 1778.52  1577.8 1806.96  1811.5 1901.95    1901 1930.61
#Mann= 3 , 0 , 0
       0      .1       0   979.9    .045       0   994.9      .1       0
Bank Sta=979.9,994.9
XS Rating Curve= 0 ,0
Exp/Cntr=0.3,0.1

Type RM Length L Ch R = 1 ,9499.2  ,504.3,500.7,497
XS GIS Cut Line= 3
     1839419.769      219340.144     1838017.336       219892.98
     1837370.918      220125.698
#Sta/Elev= 30
       0 2086.47   239.6 2009.34   284.5 1991.98   419.3 1930.58   514.1 1896.59
     619 1840.14   673.9 1816.56   773.7 1759.38   863.6 1720.89   963.4 1670.09
  1023.3 1643.34  1078.2 1605.71  1098.2 1599.53  1130.7 1596.51  1143.1 1596.12
  1145.7  1596.2  1272.9 1602.28  1327.8 1630.36  1457.6 1634.59  1497.5 1656.76
  1557.2 1698.48    1627 1741.26  1691.7 1772.92    1856 1861.36  1895.8 1887.57
  1925.7 1913.02  1965.5 1936.04  2030.2 1984.45  2159.6 2049.55  2194.5 2055.74
#Mann= 3 , 0 , 0
       0      .1       0  1130.7    .045       0  1145.7      .1       0
Bank Sta=1130.7,1145.7
XS Rating Curve= 0 ,0
Exp/Cntr=0.3,0.1

Type RM Length L Ch R = 1 ,8998.5  ,334.9,337.6,340.2
XS GIS Cut Line= 3
      1839171.27      218860.613     1838379.235       219193.18
     1837219.625      219853.939
#Sta/Elev= 30
       0 2131.93    54.9 2129.74   149.8 2095.13   244.7 2035.69   294.7 2015.32
   474.5 1902.68   619.3 1829.06   709.2 1772.62     839  1701.1     884 1680.72
    1009 1638.42    1054 1615.26    1084 1590.55  1101.6 1585.43    1114 1584.91
  1116.6 1584.95  1163.9 1590.07  1248.9  1588.5  1298.9 1600.43  1343.9  1600.6
  1398.9 1614.71  1443.9 1617.89  1583.8 1724.66  1723.8 1806.33  1808.8 1866.43
  1868.8  1894.8  1968.7 1952.85  2078.7 2000.55  2133.7 2036.31  2193.7 2063.63
#Mann= 3 , 0 , 0
       0      .1       0  1101.6    .045       0  1116.6      .1       0
Bank Sta=1101.6,1116.6
XS Rating Curve= 0 ,0
Exp/Cntr=0.3,0.1

Type RM Length L Ch R = 1 ,8661    ,383.2,385.8,388.4
XS GIS Cut Line= 4
     1839062.679      218660.346     1838085.545      218990.414
      1837601.88      219196.299     1837075.731      219591.728
#Sta/Elev= 30
       0 2037.03    64.8  2016.8   433.5 1865.18   513.2 1827.93   652.7  1756.9
   697.6  1730.9   742.4 1700.04   782.2 1679.92   936.7 1624.13  1041.3 1600.44
  1105.8 1589.57  1140.5 1569.71  1141.6 1569.79  1156.6 1571.05  1180.2 1579.54
  1229.7 1580.53  1269.4 1596.38  1299.2 1614.27  1383.5 1618.63  1408.3 1636.85
  1472.7 1699.74  1507.4 1717.05  1616.9 1790.77  1651.8 1817.24  1666.7 1825.32
  1776.4    1862  1846.2 1898.17  1881.1 1910.83  2075.6  2039.4  2215.2 2106.35
#Mann= 3 , 0 , 0
       0      .1       0  1141.6    .045       0  1156.6      .1       0
Bank Sta=1141.6,1156.6
XS Rating Curve= 0 ,0
Exp/Cntr=0.3,0.1

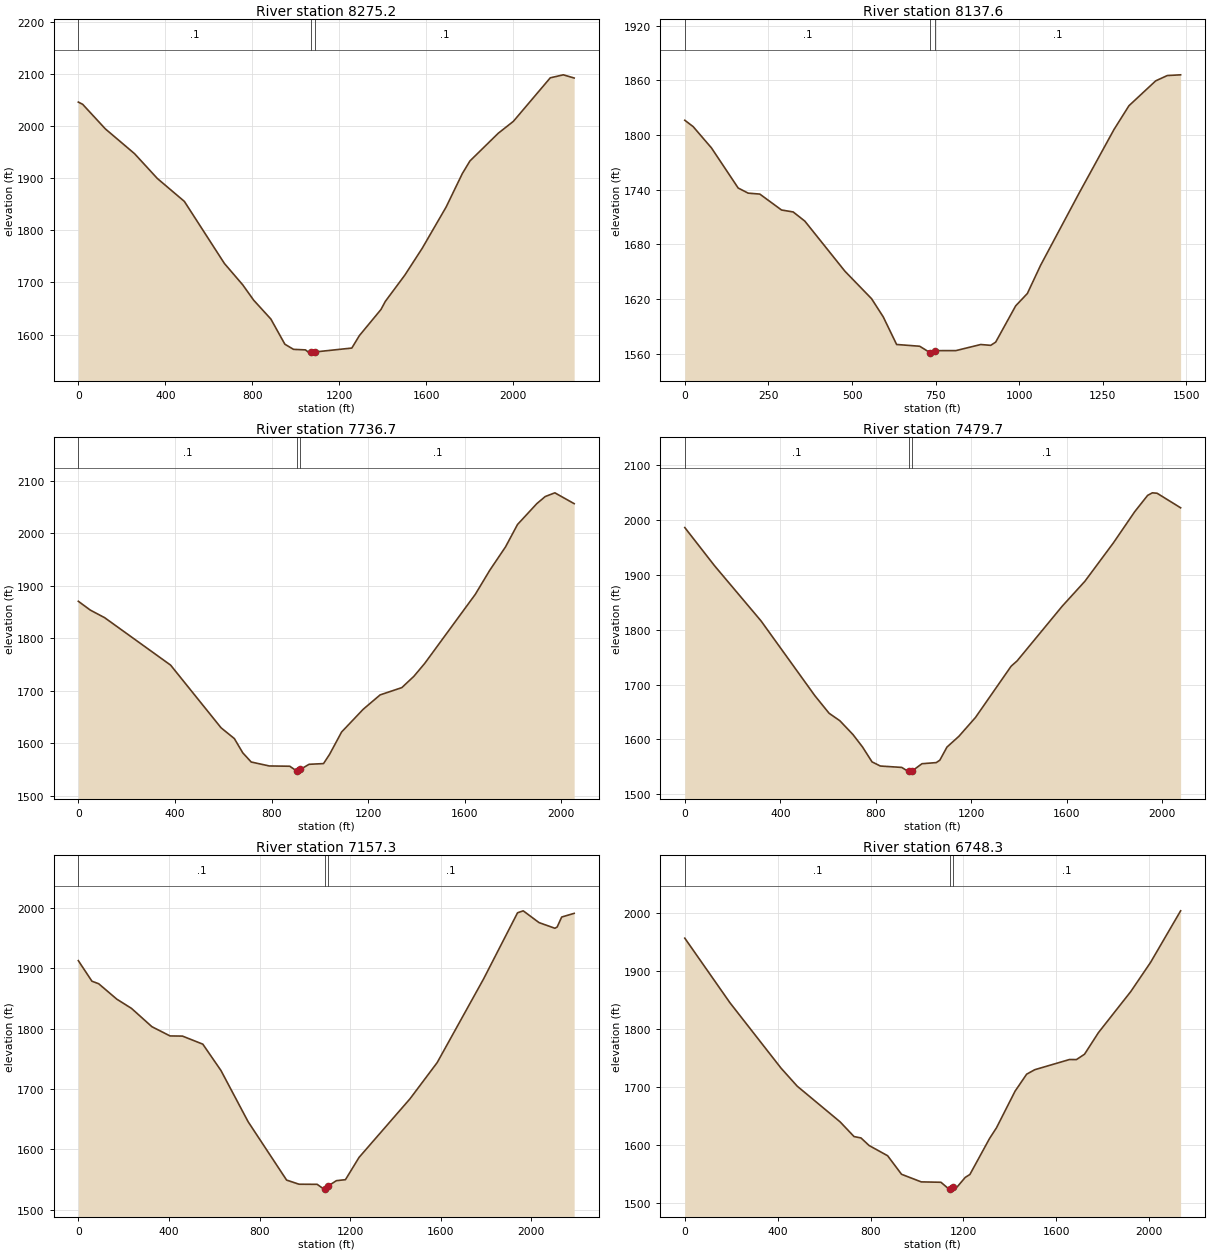
Type RM Length L Ch R = 1 ,8275.2  ,148.1,137.5,127
XS GIS Cut Line= 4
     1838945.439      218462.264     1838184.508      218587.667
     1837598.686      218759.967     1836923.053      219351.861
#Sta/Elev= 30
       0  2046.1    19.9 2041.86   124.4 1994.65   258.7 1947.08   363.2 1899.63
   487.6 1855.58   671.7 1736.54   756.3 1695.36     806 1666.25   885.4 1629.89
   949.9 1581.54   989.6 1571.74  1044.2 1570.72  1064.1  1564.5  1071.6 1565.74
  1086.6 1566.67  1257.7 1574.23  1292.5 1598.16  1391.8 1648.25  1411.8 1663.78
  1501.6 1714.22  1581.4 1765.66  1691.2 1844.66  1766.1 1909.14    1801 1933.21
  1930.8 1986.21  2000.6 2009.18  2170.3 2092.66  2230.2 2098.41  2280.1 2092.28
#Mann= 3 , 0 , 0
       0      .1       0  1071.6    .045       0  1086.6      .1       0
Bank Sta=1071.6,1086.6
XS Rating Curve= 0 ,0
Exp/Cntr=0.3,0.1

Type RM Length L Ch R = 1 ,8137.6  ,404.4,400.9,397.4
XS GIS Cut Line= 4
     1838245.035      217938.017     1837913.585      218477.724
     1837740.527      218639.049     1837212.553      218949.967
#Sta/Elev= 30
       0 1816.19    24.9 1809.26    79.8 1785.84   159.6  1741.9   189.5 1736.27
   224.4 1735.24   289.2  1717.8   324.2 1715.63   359.1 1705.54   478.8 1650.68
   558.6 1620.48   593.5 1600.55   633.4 1570.33   702.4  1568.4   734.6 1561.08
   736.9 1560.85   749.6 1563.58   810.8 1563.62   884.9 1570.29   914.8 1569.38
   929.7 1572.94   989.5 1612.71  1024.4 1626.24  1064.2 1657.34  1178.8 1736.08
  1283.4 1806.01  1328.2 1832.13    1408 1859.35  1442.8 1865.23  1482.7 1866.01
#Mann= 3 , 0 , 0
       0      .1       0   734.6    .045       0   749.6      .1       0
Bank Sta=734.6,749.6
XS Rating Curve= 0 ,0
Exp/Cntr=0.3,0.1

Type RM Length L Ch R = 1 ,7736.7  ,261.4,257,252.7
XS GIS Cut Line= 3
     1838177.944      217797.272     1837757.859      218042.322
     1836760.157      219250.067
#Sta/Elev= 30
       0 1870.25    49.6 1853.51   109.2 1839.01   382.1 1748.85   591.1 1629.59
     646 1609.11   680.9 1581.96   715.8 1564.53   790.7 1557.02   875.5 1556.51
   904.2 1547.41   905.4  1547.2   919.2 1550.43   955.3 1560.18  1015.2 1561.52
  1040.1 1579.03    1090 1621.59  1179.8 1665.01  1249.6 1692.23  1339.4 1706.05
  1389.3 1727.54  1434.2 1752.13  1643.8 1883.64  1703.6 1929.34  1768.5 1973.58
  1818.4 2016.33  1898.2 2055.98  1933.1 2069.52    1973 2076.58  2052.9 2055.99
#Mann= 3 , 0 , 0
       0      .1       0   904.2    .045       0   919.2      .1       0
Bank Sta=904.2,919.2
XS Rating Curve= 0 ,0
Exp/Cntr=0.3,0.1

Type RM Length L Ch R = 1 ,7479.7  ,324.7,322.4,320.1
XS GIS Cut Line= 4
     1837834.997      217493.667     1837333.903      218116.767
     1836841.523      219023.094     1836675.944      219206.103
#Sta/Elev= 30
       0 1986.02   124.9 1916.31   319.8 1815.74   544.7 1679.83   604.7 1647.59
   649.7 1634.02   704.6 1608.88   744.6 1586.28   784.6 1559.02   819.5 1551.43
   909.2  1548.9   934.1 1542.14     939 1542.46     954 1542.89   993.9 1555.64
  1053.7 1557.68  1068.7 1562.04  1098.6 1585.96  1148.4 1605.48  1218.2 1639.98
  1367.6  1733.4  1392.6 1743.03  1581.9 1842.88  1676.6 1888.12  1796.2 1958.21
  1885.3 2014.89  1939.6 2044.69  1959.4 2049.34  1979.1  2048.6  2077.8 2022.05
#Mann= 3 , 0 , 0
       0      .1       0     939    .045       0     954      .1       0
Bank Sta=939,954
XS Rating Curve= 0 ,0
Exp/Cntr=0.3,0.1

Type RM Length L Ch R = 1 ,7157.3  ,405.2,409.1,412.9
XS GIS Cut Line= 3
     1837385.373      217119.988      1836882.21      218323.197
     1836463.013      219102.285
#Sta/Elev= 30
       0 1912.82      60 1878.78    89.9 1874.57   169.9 1849.01   234.8 1833.68
   324.8 1803.39   404.8 1788.09   459.7 1787.81   549.6 1774.44   629.6 1730.83
   749.5 1645.96   919.4 1549.24   974.4 1542.35  1054.3 1542.19  1084.3 1534.23
  1086.8 1534.96  1101.8 1539.21  1139.3 1548.25  1179.3  1549.9  1239.2 1586.75
  1464.1 1683.87  1584.1 1743.87    1789 1882.52    1939 1992.15    1964 1995.39
  2033.9 1975.87  2103.9 1966.49  2113.9 1968.64  2133.9  1985.1  2188.9 1991.21
#Mann= 3 , 0 , 0
       0      .1       0  1086.8    .045       0  1101.8      .1       0
Bank Sta=1086.8,1101.8
XS Rating Curve= 0 ,0
Exp/Cntr=0.3,0.1

Type RM Length L Ch R = 1 ,6748.3  ,415.8,423.3,430.8
XS GIS Cut Line= 3
     1837285.264      216996.485     1836694.519      217801.648
     1836081.895      218759.967
#Sta/Elev= 30
       0 1956.69   194.7 1845.27   414.4 1732.75   484.3 1701.56   669.1 1640.07
     729 1614.75     759 1612.34   793.9 1599.32   873.8 1581.65   933.7  1549.7
  1018.6  1536.6  1103.4 1535.94  1138.3 1524.11    1142 1524.41    1157 1527.14
  1173.2 1527.84  1208.2 1544.35  1228.1 1549.32  1312.9 1611.41  1342.8 1629.88
  1422.7 1692.87  1472.6 1722.21  1507.5 1729.93  1657.1 1747.51  1687.1 1747.39
    1722 1756.63  1781.8 1793.78  1921.5  1864.8  2006.3  1914.8    2136 2003.82
#Mann= 3 , 0 , 0
       0      .1       0    1142    .045       0    1157      .1       0
Bank Sta=1142,1157
XS Rating Curve= 0 ,0
Exp/Cntr=0.3,0.1

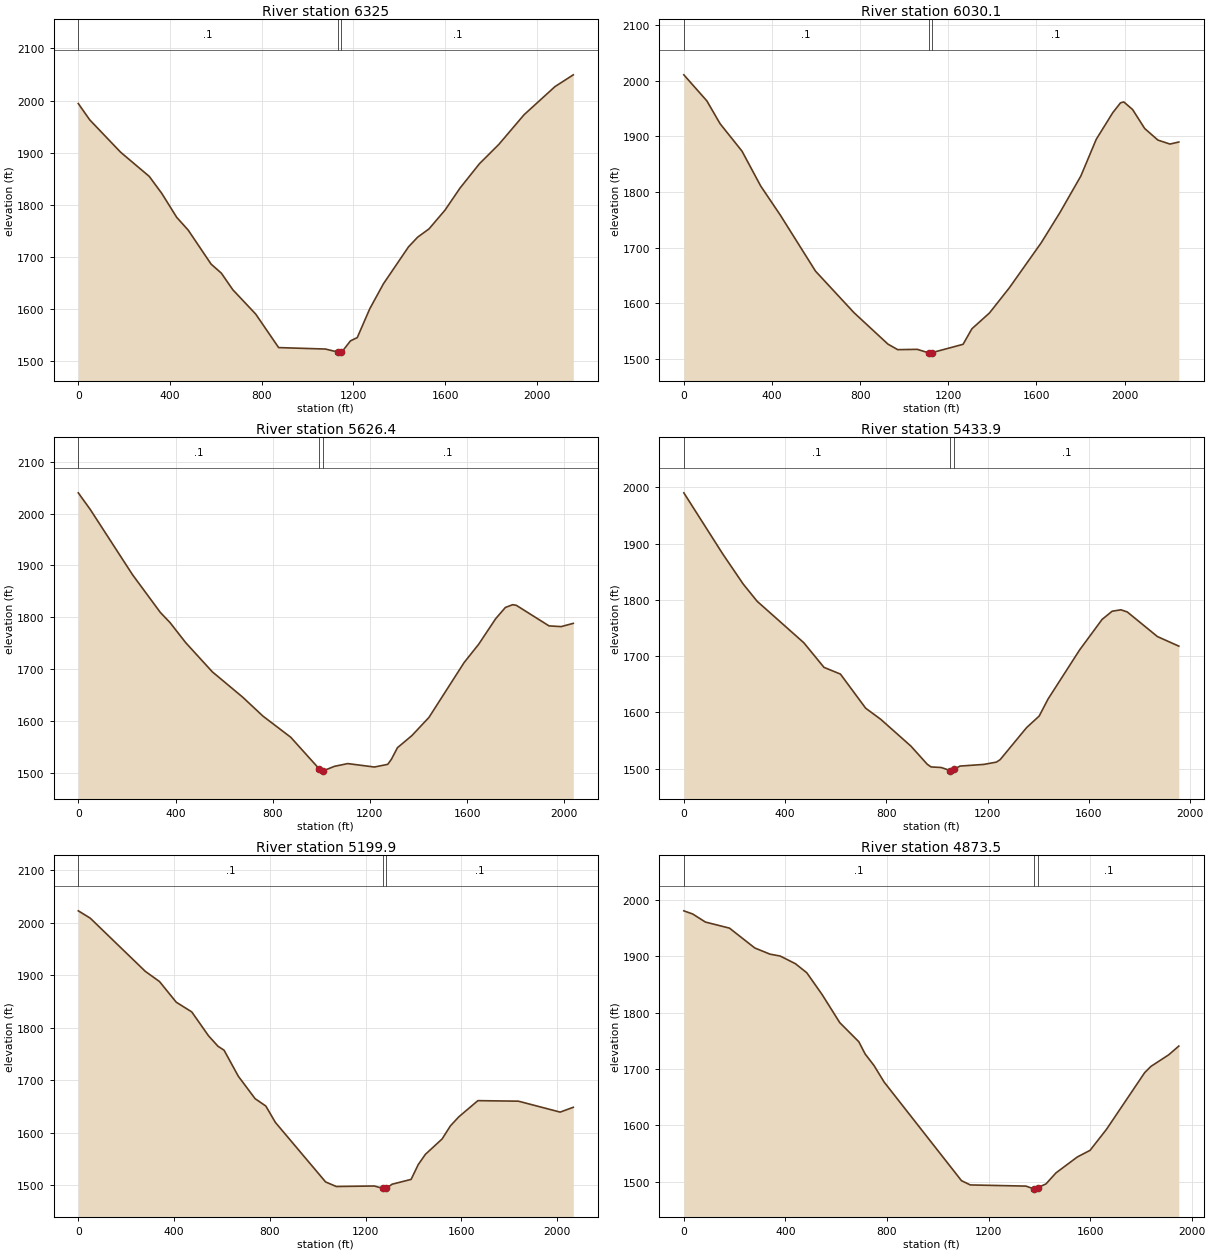
Type RM Length L Ch R = 1 ,6325    ,287,294.9,302.7
XS GIS Cut Line= 4
     1837222.791      216938.106     1836464.613      217516.543
     1836033.237      217859.684     1835693.364      218418.513
#Sta/Elev= 30
       0 1994.35    49.9 1963.04   184.7 1900.96   309.6 1854.58   364.5 1821.78
   429.4    1776   479.3 1751.64   579.2 1686.44   624.1 1668.98     674 1637.21
   773.9 1590.52   873.8  1526.3  1077.8 1523.52  1132.9  1517.6  1142.3 1515.68
  1147.9 1517.07    1187 1539.15  1216.8 1545.52  1271.4 1600.86    1331 1648.74
  1440.3  1719.5    1480    1738  1529.8 1753.99  1599.7 1790.06  1664.6    1832
  1749.5 1878.84  1834.4 1916.06  1944.2 1972.82    2079 2026.78  2158.9 2049.39
#Mann= 3 , 0 , 0
       0      .1       0  1132.9    .045       0  1147.9      .1       0
Bank Sta=1132.9,1147.9
XS Rating Curve= 0 ,0
Exp/Cntr=0.3,0.1

Type RM Length L Ch R = 1 ,6030.1  ,425.9,403.7,381.5
XS GIS Cut Line= 4
     1837173.818      216908.492     1836387.889      217307.686
     1836017.652      217432.247     1835340.022      218132.089
#Sta/Elev= 30
       0 2011.01   104.6 1964.04   164.4  1923.1     264 1873.61   348.6    1811
   438.3 1758.21   597.6 1657.61   771.9 1582.98     926 1526.33   970.5 1516.29
  1059.5 1516.84  1110.8 1510.57  1113.9 1510.03  1125.8 1510.87  1267.2 1525.91
  1307.1  1553.8    1387 1582.32    1477 1627.53  1621.8 1708.67  1706.8 1763.12
  1801.7  1828.9  1871.6    1895  1946.5 1942.83  1981.5 1960.52  1996.5 1962.25
  2036.5 1948.54  2091.4 1914.38  2151.4 1893.53  2206.3 1886.39  2246.3 1890.08
#Mann= 3 , 0 , 0
       0      .1       0  1110.8    .045       0  1125.8      .1       0
Bank Sta=1110.8,1125.8
XS Rating Curve= 0 ,0
Exp/Cntr=0.3,0.1

Type RM Length L Ch R = 1 ,5626.4  ,195.8,192.4,189.1
XS GIS Cut Line= 5
     1836735.777      216436.629      1836324.81      216688.018
     1836024.612      216940.734     1835963.016      217146.057
      1835257.33      217779.254
#Sta/Elev= 30
       0 2040.22    49.7 2007.75   223.5 1881.87   337.7 1809.23   377.5 1789.64
     442 1750.88   551.3 1694.68   675.5 1646.03   759.9 1609.05   874.2 1568.22
     990 1507.89  1003.8 1502.85    1005 1502.86  1053.6 1512.06  1108.5 1517.41
  1218.3 1510.78  1273.2 1515.95  1288.1 1525.59  1313.1 1548.03    1373 1571.65
  1442.8 1606.58  1587.5 1712.52  1647.4 1747.85  1717.3 1797.18  1757.2 1818.87
  1787.1 1824.21  1802.1 1823.05  1936.8 1783.29  1986.8 1781.91  2036.6 1788.19
#Mann= 3 , 0 , 0
       0      .1       0     990    .045       0    1005      .1       0
Bank Sta=990,1005
XS Rating Curve= 0 ,0
Exp/Cntr=0.3,0.1

Type RM Length L Ch R = 1 ,5433.9  ,226.7,234.1,241.5
XS GIS Cut Line= 5
     1836562.877      216392.252     1835988.894      216832.231
     1835821.465      216878.986     1835768.506      217247.624
     1835221.294      217660.664
#Sta/Elev= 30
       0 1990.24   154.6 1880.96   234.4 1828.11   289.3 1797.51   473.8 1723.71
   553.6 1679.92   618.5 1667.96   718.2  1607.3   777.8 1587.51     897 1539.86
   961.6 1507.55   976.5 1502.86  1016.2 1501.88  1052.7 1496.34    1056  1495.4
  1067.7 1498.92  1090.7 1504.36  1185.1 1507.36  1234.7 1511.46  1249.6 1515.91
  1353.9 1572.84  1403.6 1593.36  1438.4 1623.46  1562.6 1710.47    1652 1765.15
  1691.8 1779.73  1726.5 1782.23  1751.4 1778.45  1870.6 1734.66  1955.1 1717.64
#Mann= 3 , 0 , 0
       0      .1       0  1052.7    .045       0  1067.7      .1       0
Bank Sta=1052.7,1067.7
XS Rating Curve= 0 ,0
Exp/Cntr=0.3,0.1

Type RM Length L Ch R = 1 ,5199.9  ,305.6,326.4,347.2
XS GIS Cut Line= 4
     1836584.092      216285.264     1835680.241      216785.528
     1835518.558      217104.073     1835075.499      217616.668
#Sta/Elev= 30
       0  2022.7    49.9 2008.75   279.5 1907.56   339.4 1887.87   409.2 1848.59
   474.1 1830.04     544  1784.6   583.9  1764.5   608.9 1757.15   668.7 1707.38
   738.6 1664.77   783.5 1650.66   823.4 1619.47  1033.1 1506.06  1077.7 1497.35
  1236.5 1498.32    1271 1493.94  1281.1 1492.35    1286 1493.61  1310.9 1501.72
  1390.3 1510.89  1420.2 1539.17  1450.1 1558.68  1519.8 1587.94  1554.7    1613
  1589.6 1630.11  1669.3 1660.96  1838.7 1659.95    2013 1639.13  2067.8  1648.3
#Mann= 3 , 0 , 0
       0      .1       0    1271    .045       0    1286      .1       0
Bank Sta=1271,1286
XS Rating Curve= 0 ,0
Exp/Cntr=0.3,0.1

Type RM Length L Ch R = 1 ,4873.5  ,357.7,361,364.2
XS GIS Cut Line= 5
      1836581.37      216187.758     1835702.623      216651.585
      1835434.96      216773.677     1835188.654      216826.339
     1834779.086      216819.743
#Sta/Elev= 30
       0 1981.02      35 1975.37    84.9 1961.11   179.8 1950.29   279.6 1915.04
   339.5  1904.1   379.5 1900.76   439.4 1887.16   484.3 1871.04   544.3 1832.57
   614.2 1782.48   689.1 1748.64     714 1726.91     749 1706.37   788.9 1677.01
  1093.4 1502.01  1128.3 1494.46  1347.1 1492.39  1379.7 1487.32  1381.7 1487.02
  1394.7 1489.82  1426.1 1496.26  1465.6 1515.86  1549.7 1544.14  1599.7 1555.84
  1664.6 1593.28  1814.5 1693.59  1839.4 1704.85  1909.4 1725.42  1949.3 1740.96
#Mann= 3 , 0 , 0
       0      .1       0  1379.7    .045       0  1394.7      .1       0
Bank Sta=1379.7,1394.7
XS Rating Curve= 0 ,0
Exp/Cntr=0.3,0.1