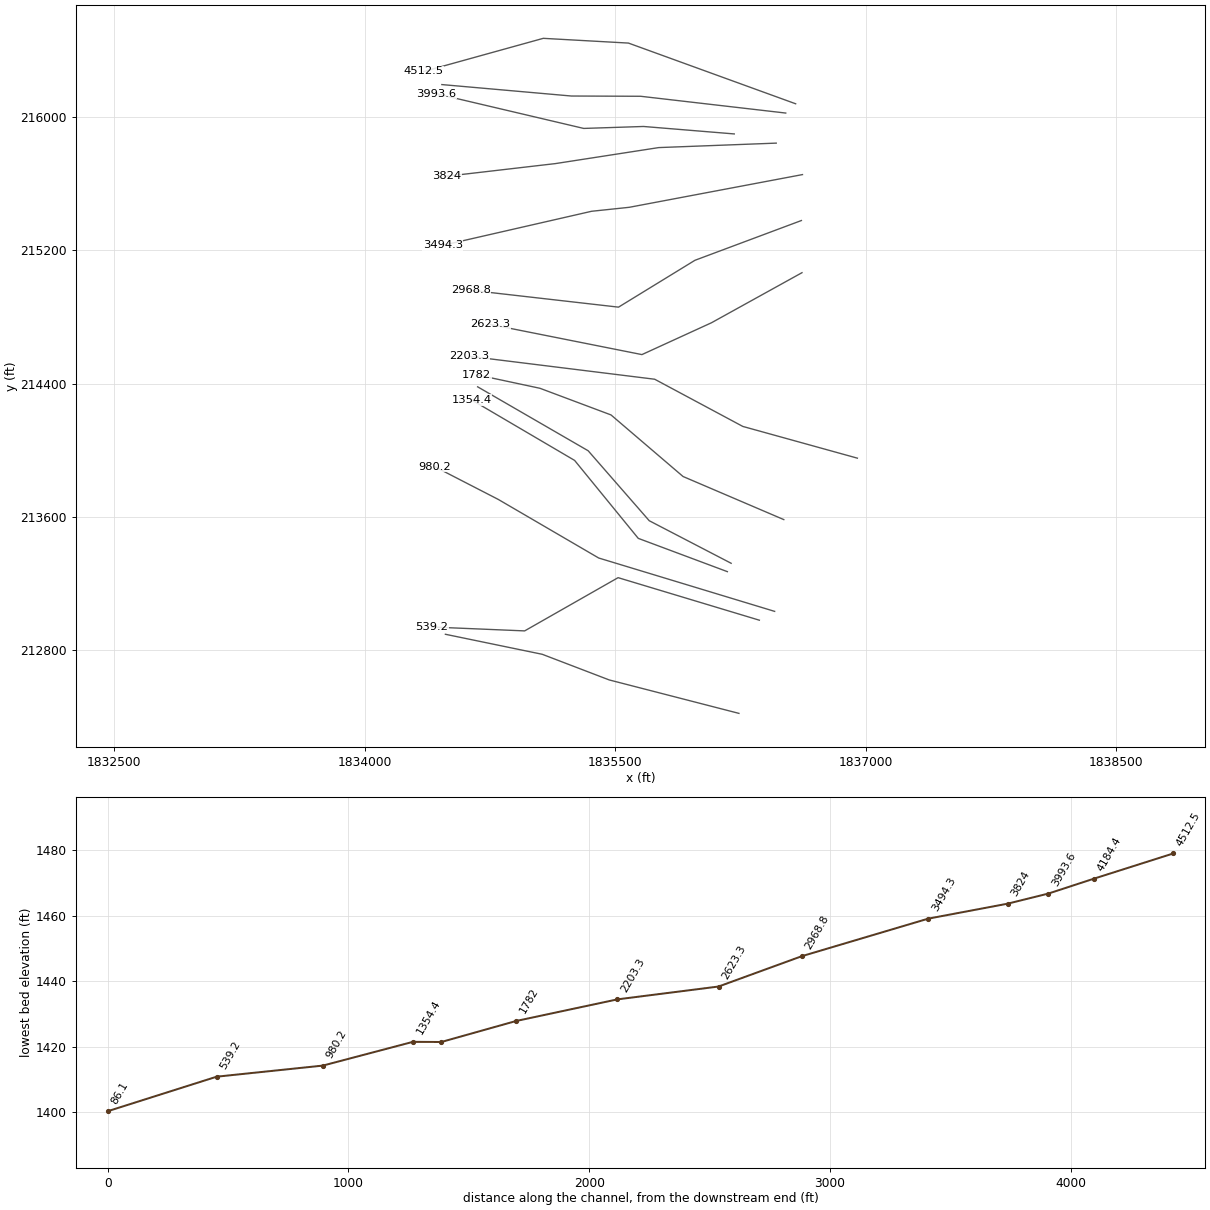
HEC-RAS study CabinCr.prj: CabinCr

--- CabinCr.g01 (geometry) --- (continued)

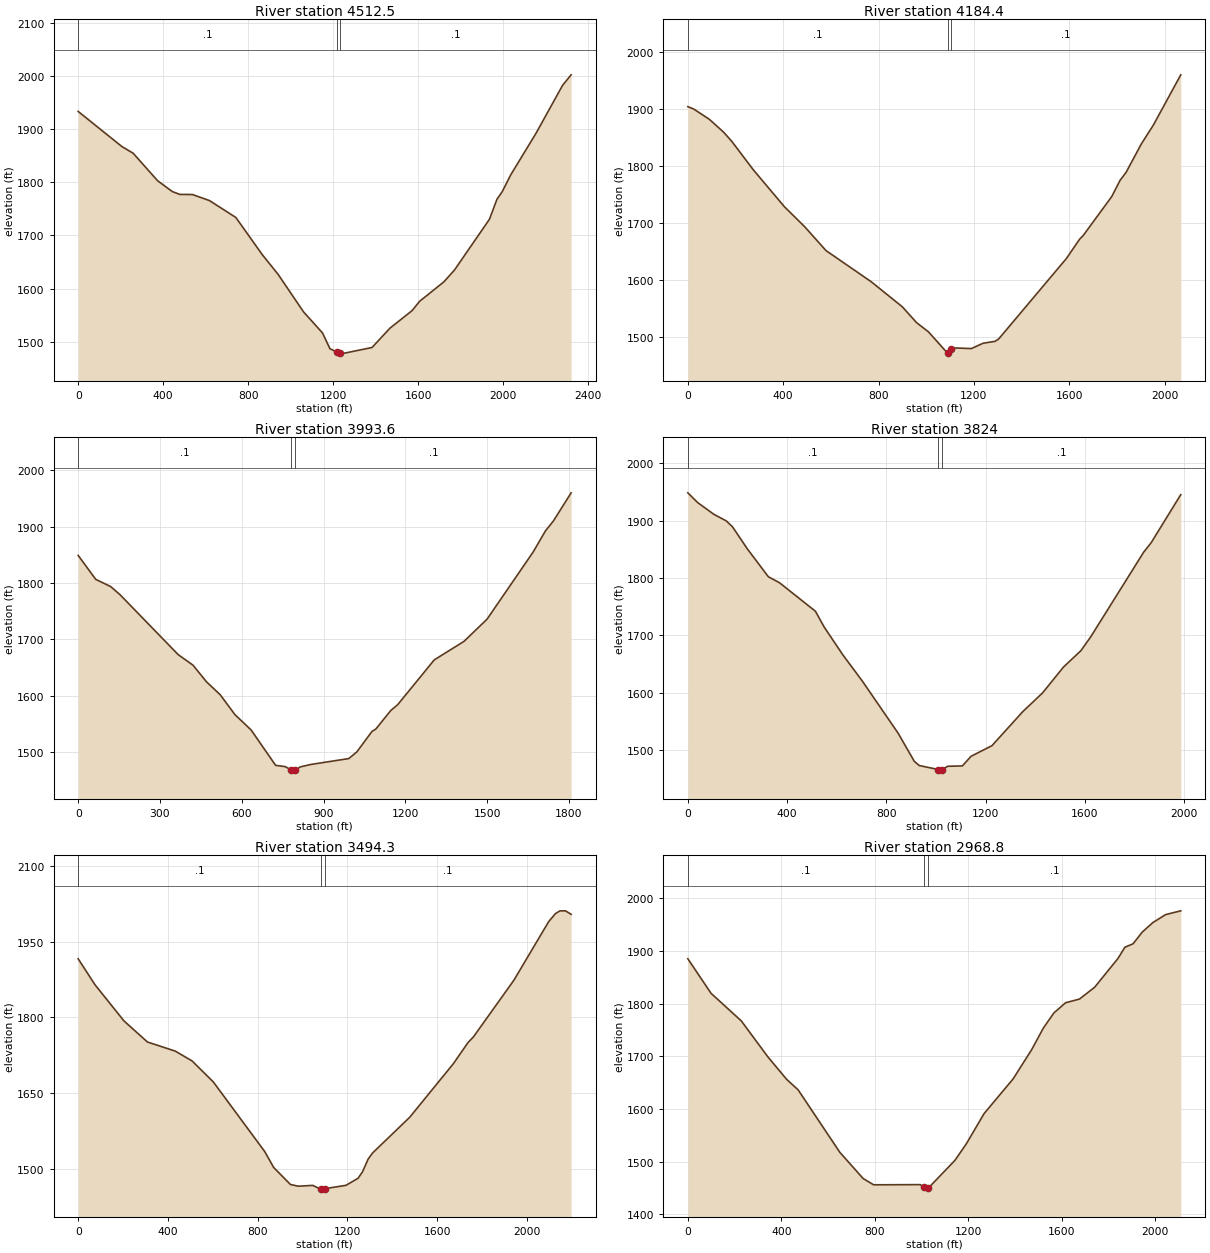
Type RM Length L Ch R = 1 ,4512.5  ,326.8,328.2,329.5
XS GIS Cut Line= 4
     1836580.494      216079.597     1835579.569      216443.736
     1835069.823       216472.17     1834353.988       216273.36
#Sta/Elev= 30
       0 1933.04   204.1 1867.55   258.8 1854.44   373.3 1802.93     443 1782.43
   477.8 1777.15   537.5 1776.93   617.2 1765.61   741.6 1733.83     866  1663.9
   940.7 1626.77  1060.1 1556.37  1149.4 1516.81  1184.1 1487.28  1215.5 1481.05
  1230.5 1480.09  1253.5 1478.93  1382.3 1489.54  1466.6 1525.86  1570.7 1558.84
  1605.6 1576.16  1720.2  1612.9  1770.1 1635.16  1934.6 1730.55  1969.6 1767.91
  1994.5 1782.29  2034.4  1813.8    2154 1892.35  2278.7 1982.28  2318.6 2001.83
#Mann= 3 , 0 , 0
       0      .1       0  1215.5    .045       0  1230.5      .1       0
Bank Sta=1215.5,1230.5
XS Rating Curve= 0 ,0
Exp/Cntr=0.3,0.1

Type RM Length L Ch R = 1 ,4184.4  ,189.9,190.8,191.6
XS GIS Cut Line= 4
     1836521.292      216023.932     1835652.649      216124.607
     1835238.205       216126.11     1834462.658      216194.787
#Sta/Elev= 30
       0 1904.19      25 1899.95    89.9 1882.07   149.9  1859.5   184.9 1842.96
   274.8  1793.2   404.8 1728.58   489.7 1693.48   579.6 1651.39   769.5 1596.58
   899.4 1552.75   959.3 1524.88  1009.3 1508.68  1089.2 1471.28  1090.5 1471.78
  1105.5 1478.17  1124.1  1480.3    1189 1479.27    1239 1488.71  1288.9 1492.04
  1303.9 1496.21  1588.4 1637.77  1643.3 1671.43  1658.2  1677.8    1778 1746.29
    1813 1774.82  1837.9 1788.61  1902.8  1839.2  1952.7 1871.96  2067.5 1960.11
#Mann= 3 , 0 , 0
       0      .1       0  1090.5    .045       0  1105.5      .1       0
Bank Sta=1090.5,1105.5
XS Rating Curve= 0 ,0
Exp/Cntr=0.3,0.1

Type RM Length L Ch R = 1 ,3993.6  ,166.9,169.6,172.3
XS GIS Cut Line= 4
     1836213.098      215898.711     1835669.697       215943.45
     1835311.848      215931.717     1834430.876      216139.515
#Sta/Elev= 30
       0 1848.85    64.4 1806.45     119 1793.73   153.7 1779.19   366.8 1673.12
   421.3 1654.39   470.9 1624.86   520.5 1602.31   575.1 1566.82   634.8 1539.41
   724.3  1476.9   759.1 1474.74   782.2 1468.68   788.9  1466.7   797.2 1468.08
   813.8 1474.09   853.6 1478.51   992.8 1488.96  1022.6 1500.94  1077.4 1536.78
  1092.3 1541.47    1147 1574.22  1171.8  1584.2  1306.1  1663.7  1415.5 1696.62
  1500.1 1735.99  1669.2 1854.95  1713.9 1892.06  1743.8 1910.14  1808.4 1959.75
#Mann= 3 , 0 , 0
       0      .1       0   782.2    .045       0   797.2      .1       0
Bank Sta=782.2,797.2
XS Rating Curve= 0 ,0
Exp/Cntr=0.3,0.1

Type RM Length L Ch R = 1 ,3824    ,330.8,329.7,328.6
XS GIS Cut Line= 4
      1836464.34      215843.585      1835760.82      215816.784
     1835142.169      215720.748     1834490.017      215644.813
#Sta/Elev= 30
       0 1948.19    39.9 1931.11   104.9  1910.8   154.8 1899.36   179.8 1889.14
   239.7  1850.7   324.6 1802.04   369.5 1791.62   514.3 1741.99   549.2 1714.72
   624.1 1666.49     704 1619.95   848.1 1529.32   912.7 1480.65   932.6 1473.39
  1009.4  1466.4  1017.1 1463.61  1024.4 1465.57  1046.9 1472.06  1106.5 1472.68
  1141.3 1489.41  1225.8 1507.97    1350 1567.25  1429.6  1599.8  1514.1  1644.9
  1583.8 1673.17  1623.6 1697.37  1837.4 1845.04  1867.3 1861.32  1986.6 1945.03
#Mann= 3 , 0 , 0
       0      .1       0  1009.4    .045       0  1024.4      .1       0
Bank Sta=1009.4,1024.4
XS Rating Curve= 0 ,0
Exp/Cntr=0.3,0.1

Type RM Length L Ch R = 1 ,3494.3  ,515.3,525.5,535.7
XS GIS Cut Line= 4
     1836621.422      215654.831     1835584.452      215458.598
     1835359.107      215434.763     1834467.711      215230.321
#Sta/Elev= 30
       0  1916.4    74.7 1865.01   204.1 1793.02   308.6 1751.19   433.1 1733.02
   507.8 1713.48   602.4 1671.78   831.4 1533.54   871.2 1502.03   945.8 1468.23
   980.7 1464.86  1045.4 1466.47    1080 1459.05  1082.8 1459.05  1097.8 1459.81
  1193.3  1466.6  1247.5 1480.74  1267.2  1493.7    1292 1518.71    1312 1530.91
  1476.9 1601.56  1671.8 1708.16  1736.8 1749.92  1761.7 1761.65  1941.6 1873.95
  2096.6 1990.25  2126.6 2006.13  2146.5 2011.54  2171.5 2011.66  2196.5 2004.78
#Mann= 3 , 0 , 0
       0      .1       0  1082.8    .045       0  1097.8      .1       0
Bank Sta=1082.8,1097.8
XS Rating Curve= 0 ,0
Exp/Cntr=0.3,0.1

Type RM Length L Ch R = 1 ,2968.8  ,348.3,345.5,342.8
XS GIS Cut Line= 4
     1836614.942      215379.267      1835977.68      215140.702
     1835520.159      214859.654      1834634.53      214960.962
#Sta/Elev= 30
       0 1885.07    99.3 1819.48   228.5  1767.2   342.7 1698.63   422.2 1656.34
   471.8 1636.16   650.6 1517.32   750.1 1467.73   794.8 1455.81   993.7 1456.14
  1012.3 1451.31  1023.5  1447.6  1027.3 1448.85  1142.8 1502.29  1192.5 1534.43
  1267.2  1590.9  1391.7 1656.99  1471.4 1712.81  1521.2 1753.64    1566 1782.18
  1615.8  1801.5  1675.6 1808.54  1740.3 1830.96  1839.9 1885.49  1869.8 1906.95
  1904.6 1913.47  1944.5 1935.95  1989.3 1953.73  2044.1 1968.96  2108.8  1976.1
#Mann= 3 , 0 , 0
       0      .1       0  1012.3    .045       0  1027.3      .1       0
Bank Sta=1012.3,1027.3
XS Rating Curve= 0 ,0
Exp/Cntr=0.3,0.1

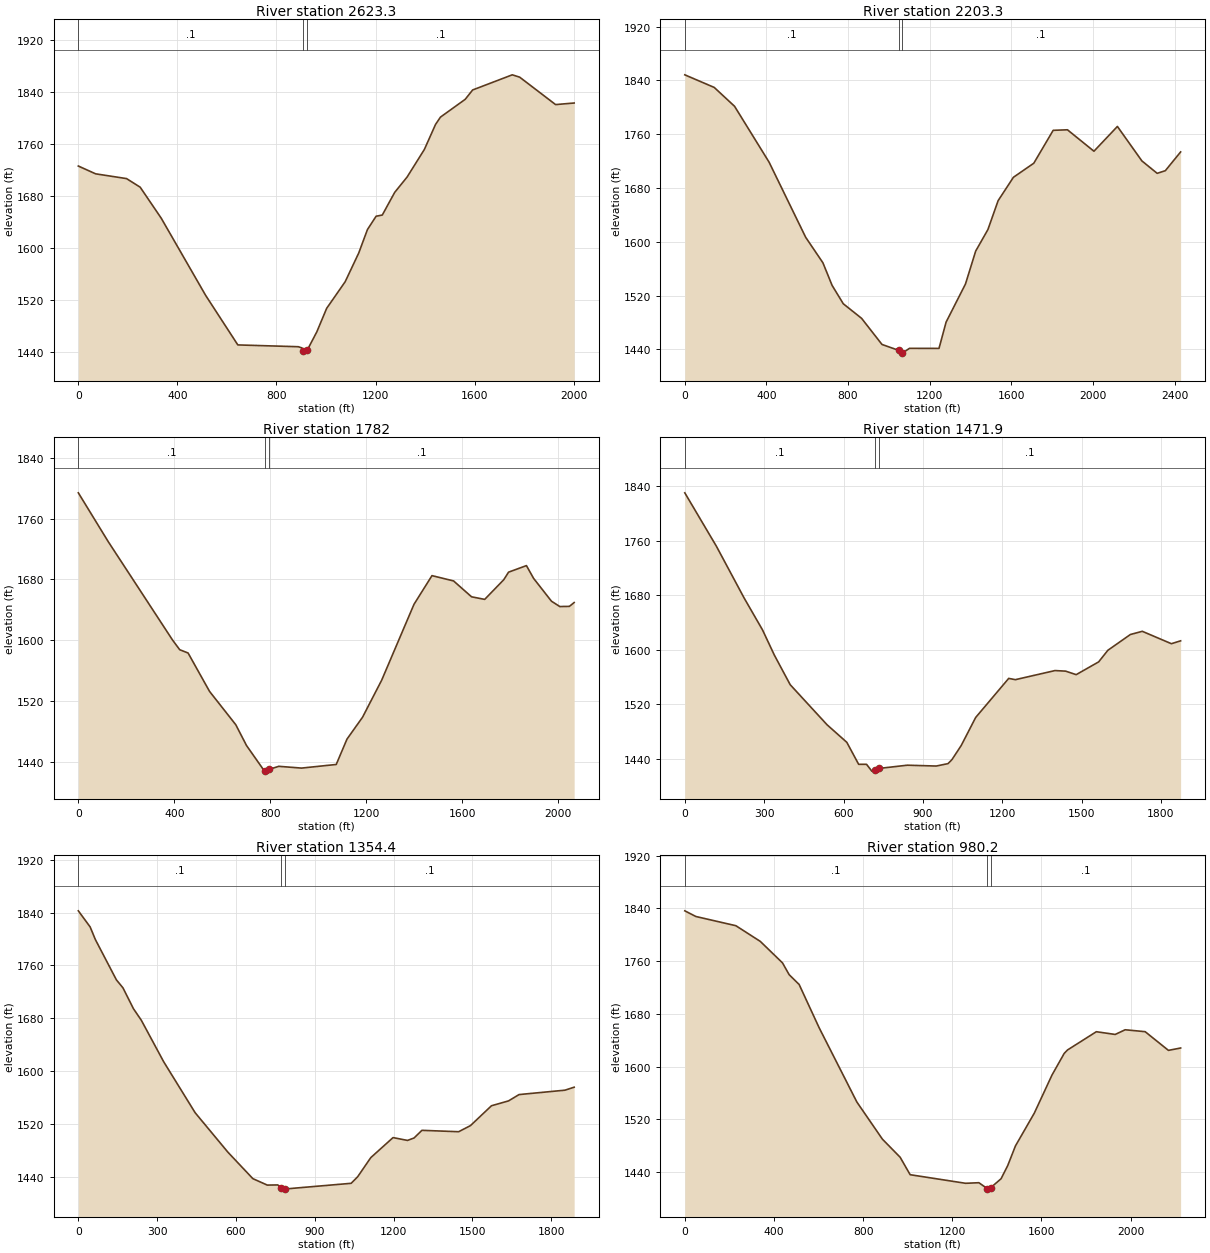
Type RM Length L Ch R = 1 ,2623.3  ,441.2,420,398.8
XS GIS Cut Line= 4
     1836618.445      215066.363     1836076.938       214766.14
     1835660.317      214575.016     1834753.558      214755.921
#Sta/Elev= 30
       0 1726.13    69.9 1714.14   194.7 1706.81   249.7 1693.61   334.6    1646
   514.3 1527.08   644.1 1450.98   888.2 1448.21   903.2 1446.33     909 1441.77
   913.1 1438.36     924 1442.66   962.9 1470.96  1002.8 1507.24  1077.5 1548.14
  1132.5 1592.52  1167.5 1628.43  1202.5 1648.92  1227.5 1650.77  1277.4 1685.55
  1327.4  1709.1  1397.4 1751.66  1442.4 1790.09  1462.4 1801.38  1562.3 1828.76
  1592.3 1843.13  1752.3 1866.42  1782.2 1862.83  1927.2 1820.65  2002.2 1823.06
#Mann= 3 , 0 , 0
       0      .1       0     909    .045       0     924      .1       0
Bank Sta=909,924
XS Rating Curve= 0 ,0
Exp/Cntr=0.3,0.1

Type RM Length L Ch R = 1 ,2203.3  ,426.4,421.2,416
XS GIS Cut Line= 4
      1836950.05      213953.751     1836264.221      214144.106
     1835736.713      214427.227     1834626.036      214565.012
#Sta/Elev= 30
       0 1848.23   144.3 1829.47   243.9 1801.44   413.1 1718.34   592.3  1606.7
   676.9  1568.7   721.7 1535.22   776.6 1507.86   866.4 1486.14   966.2 1447.35
  1047.5 1438.62  1062.5  1434.5    1066 1434.45  1100.9 1441.54  1245.6 1441.46
  1280.5 1480.61  1375.4 1537.26  1425.4 1586.16  1485.3 1618.18  1535.3  1661.1
  1610.2 1695.86  1710.2 1716.82  1805.1  1765.7    1875 1766.51  2004.9 1734.64
  2119.8 1771.48  2239.8 1720.23  2314.7 1701.77  2354.7  1705.7  2429.6 1733.58
#Mann= 3 , 0 , 0
       0      .1       0  1047.5    .045       0  1062.5      .1       0
Bank Sta=1047.5,1062.5
XS Rating Curve= 0 ,0
Exp/Cntr=0.3,0.1

Type RM Length L Ch R = 1 ,1782    ,313.6,310.2,306.7
XS GIS Cut Line= 5
     1836509.597      213585.225     1835906.545      213843.675
      1835475.22      214213.111     1835049.966      214372.884
     1834670.905      214454.111
#Sta/Elev= 30
       0 1793.87   124.3 1729.81   392.7 1600.19   422.5 1587.51   457.3 1583.21
   546.8  1532.7   656.1 1488.86   700.9 1461.48   775.7 1427.85   778.6 1428.07
   793.6 1430.03   835.4 1434.17   930.1 1431.85  1074.6  1436.6  1119.4 1469.93
  1184.2  1498.7    1264 1547.47  1398.7 1647.28  1473.6 1684.96  1563.5    1678
  1638.4 1657.13  1693.2 1653.72  1772.7 1679.59  1792.6 1689.51  1867.2 1698.15
    1897 1681.37  1971.5 1651.31  2006.3  1644.3  2046.1 1644.53    2066 1649.57
#Mann= 3 , 0 , 0
       0      .1       0   778.6    .045       0   793.6      .1       0
Bank Sta=778.6,793.6
XS Rating Curve= 0 ,0
Exp/Cntr=0.3,0.1

Type RM Length L Ch R = 1 ,1471.9  ,118.3,117.5,116.7
XS GIS Cut Line= 4
     1836194.396      213323.153     1835704.092      213578.456
     1835338.446      213998.197     1834676.802      214381.783
#Sta/Elev= 30
       0 1830.06   119.5 1751.61   224.1 1675.75   293.8 1628.79   338.6 1591.73
   398.4 1548.37   537.8  1489.5   612.4 1463.76   657.2 1431.46     687 1431.44
   706.9 1421.46   719.9 1423.36   734.9 1425.44   841.1 1430.16   950.4 1428.94
   995.1 1432.48    1010 1438.44  1044.8 1459.04  1099.5 1500.23  1224.4 1557.63
  1249.4 1555.73  1399.4  1569.1  1439.4 1568.26  1479.4  1563.1  1564.3 1581.83
  1599.3  1598.9  1684.3 1622.04  1729.3 1626.74  1839.3 1608.55  1874.2 1612.75
#Mann= 3 , 0 , 0
       0      .1       0   719.9    .045       0   734.9      .1       0
Bank Sta=719.9,734.9
XS Rating Curve= 0 ,0
Exp/Cntr=0.3,0.1

Type RM Length L Ch R = 1 ,1354.4  ,366,374.2,382.4
XS GIS Cut Line= 4
     1836171.765      213272.945     1835638.403      213472.616
     1835257.342      213940.287     1834641.888      214302.541
#Sta/Elev= 30
       0 1842.67      45 1818.26    64.9 1799.15   144.9 1738.18   169.8 1726.13
   209.8 1694.52   239.8 1677.02   324.7 1614.35   444.6  1537.1   569.5 1477.28
   664.2 1437.36   719.1 1427.61     759 1427.85   772.7 1423.62   783.9 1421.51
   787.7 1421.77  1038.2 1430.31  1063.1 1440.27    1113  1469.2  1197.7  1499.5
  1252.7 1495.21  1277.6 1498.89  1307.6 1510.49  1447.4 1508.39  1492.4 1517.66
  1572.3 1547.69  1637.2 1555.04  1677.2  1564.6    1852 1571.25  1886.9 1575.76
#Mann= 3 , 0 , 0
       0      .1       0   772.7    .045       0   787.7      .1       0
Bank Sta=772.7,787.7
XS Rating Curve= 0 ,0
Exp/Cntr=0.3,0.1

Type RM Length L Ch R = 1 ,980.2   ,417.2,441,464.8
XS GIS Cut Line= 4
       1836454.8      213034.683      1835401.46      213354.813
      1834800.67      213706.081     1834420.332      213902.307
#Sta/Elev= 30
       0 1836.21    49.8  1827.6   229.2 1813.65   338.7 1789.89   438.4 1757.29
   468.3 1739.38   513.1 1724.54   602.8 1658.96   772.1 1546.33   886.7 1490.04
   966.4 1462.56  1011.2 1436.13    1260 1423.11  1319.6 1423.99  1357.1  1415.1
  1364.4 1414.27  1372.1 1416.31  1419.1 1430.01  1448.9 1449.89  1483.7  1479.8
  1568.2 1529.44  1647.7 1587.25  1702.4 1620.03  1717.3 1625.24  1846.6 1652.92
  1931.2 1648.79    1976 1655.88  2065.6 1652.99  2170.1 1624.64  2224.8 1628.22
#Mann= 3 , 0 , 0
       0      .1       0  1357.1    .045       0  1372.1      .1       0
Bank Sta=1357.1,1372.1
XS Rating Curve= 0 ,0
Exp/Cntr=0.3,0.1

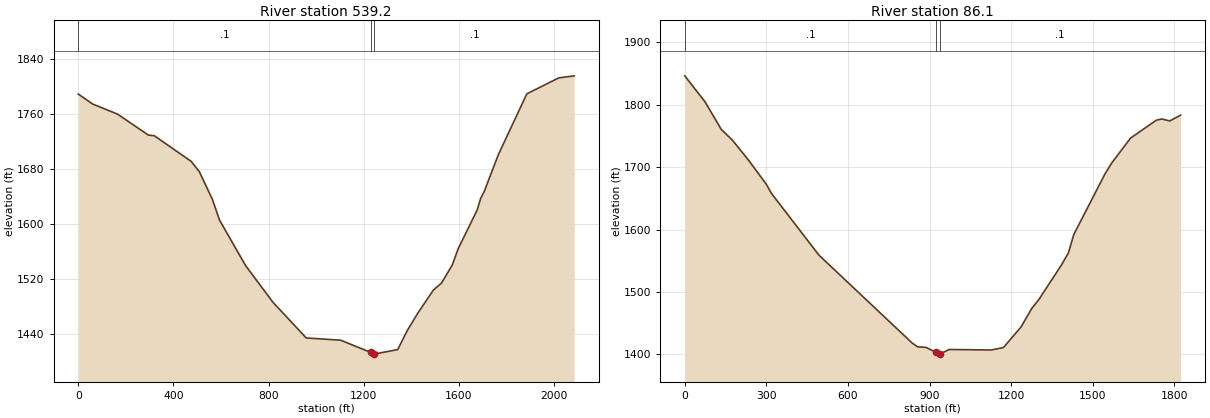
Type RM Length L Ch R = 1 ,539.2   ,473.3,453,432.8
XS GIS Cut Line= 4
     1836363.263      212981.738     1835517.638      213236.931
     1834958.277       212917.56     1834401.697      212940.933
#Sta/Elev= 30
       0 1789.52    59.9 1775.12   164.7 1760.41   294.4 1729.87   319.4  1728.9
   474.1 1691.67     509 1676.39   563.9    1636   593.8 1605.95   703.6  1539.6
   818.4 1486.34   958.2 1434.43    1103 1431.15  1230.1 1413.28  1242.8 1410.89
  1245.1 1411.09  1342.7  1417.5  1382.6    1445  1427.5 1470.69  1492.4  1504.1
  1527.4 1514.58  1572.2 1540.83    1597 1564.42  1676.6 1620.65  1691.5 1637.62
  1706.5 1647.79  1766.2  1701.6  1885.5 1789.87  2019.8 1813.13  2084.5 1816.12
#Mann= 3 , 0 , 0
       0      .1       0  1230.1    .045       0  1245.1      .1       0
Bank Sta=1230.1,1245.1
XS Rating Curve= 0 ,0
Exp/Cntr=0.3,0.1

Type RM Length L Ch R = 1 ,86.1    ,86.3,86.1,86
XS GIS Cut Line= 4
      1836241.04      212422.807     1835464.485      212623.411
     1835063.504      212777.258     1834483.919      212897.314
#Sta/Elev= 30
       0 1846.41    74.7 1804.54   134.5 1760.31   174.4  1743.7   234.1 1711.38
   298.9 1673.18   318.8 1657.88   493.2 1559.05     837 1417.82     857 1411.92
     887 1411.17   922.8 1403.39   936.9 1400.36   937.8 1400.41   971.8 1407.78
  1126.7 1407.02  1171.6 1410.83  1236.5 1443.87  1276.3 1473.86  1301.2 1487.29
  1385.7 1543.54  1410.6 1562.46  1430.5 1592.05  1544.9 1688.94  1569.8 1706.59
  1639.4 1746.66  1733.9 1775.23  1753.8  1777.3  1783.6 1774.09  1823.4 1783.46
#Mann= 3 , 0 , 0
       0      .1       0   922.8    .045       0   937.8      .1       0
Bank Sta=922.8,937.8
XS Rating Curve= 0 ,0
Exp/Cntr=0.3,0.1

Chan Stop Cuts=-1
Use User Specified Reach Order=0